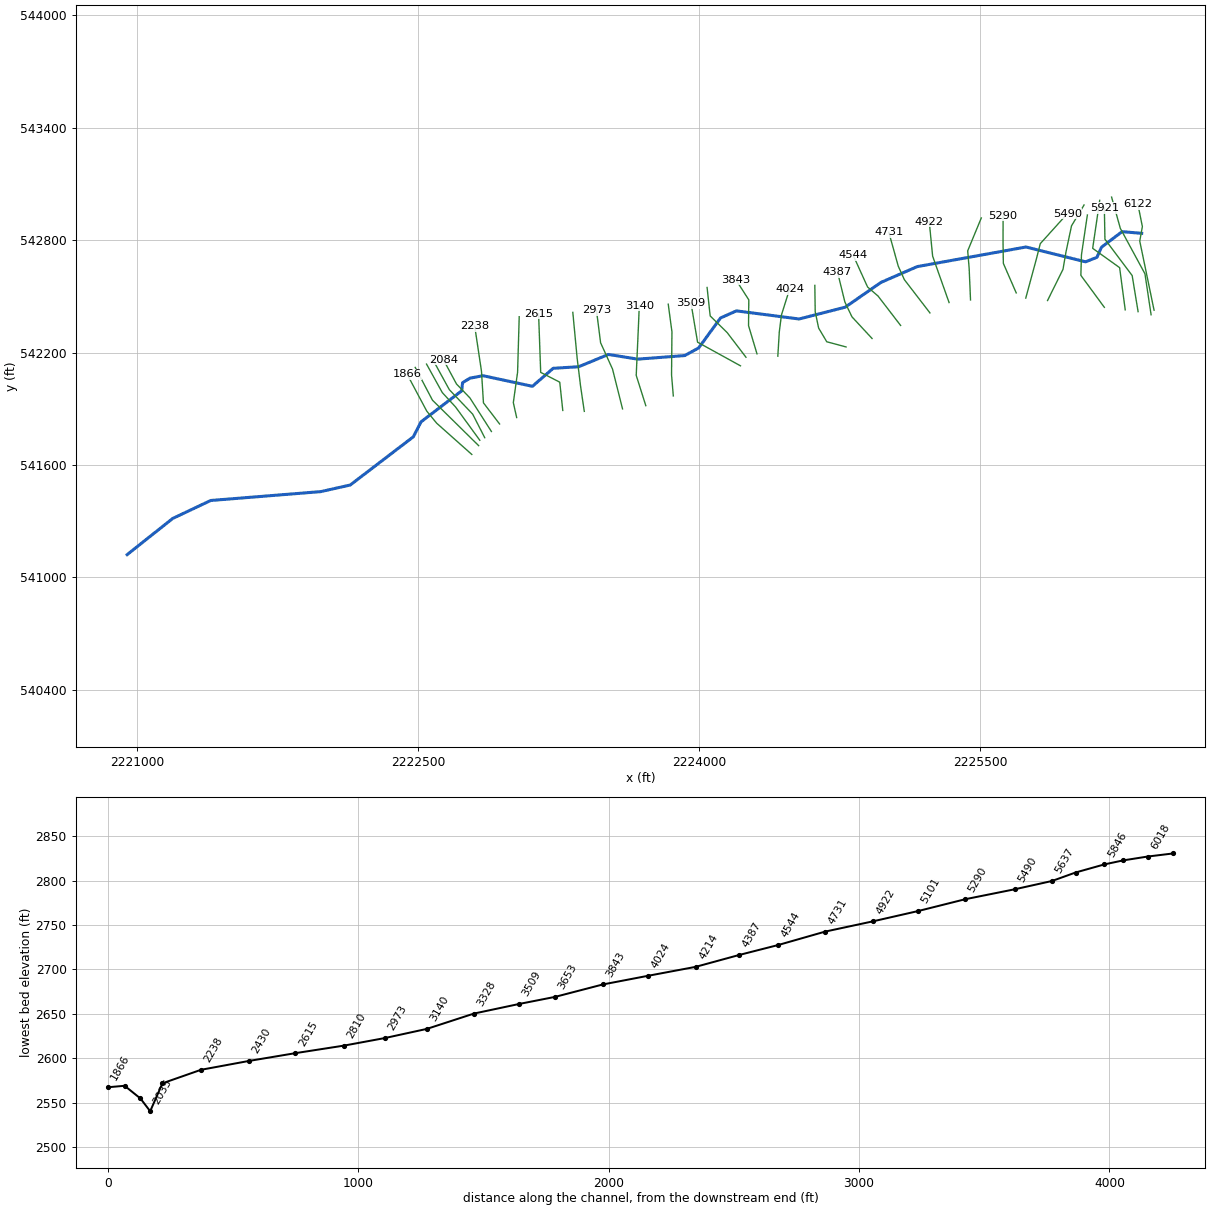
--- FALLSPRN.prj (project) ---

Proj Title=FALLSPRN
Current Plan=p01
Default Exp/Contr=0,0
English Units
Geom File=g01
Flow File=f01
Plan File=p01
Background Map Layer=Inundation Boundary (P100yr Value_0)
BEGIN DESCRIPTION:
----------MODEL BY WOOD PLC 2022----------
AFH study
Randolph County, WV
HEC-RAS Version: RAS 6.2
Vertical Datum: NAVD88
Projection: NAD 1983 StatePlane West Virginia S FIPS 4702 (US Feet)
Terrain: 1-meter LIDAR (FEMA Region III 3DEP collected 2016-2018)
Land Use: 2019 NLCD
Hydrologic Method:
WV SIR2010-5033 regression equations
Additional Model Notes:
Channel indistinct due to karst
END DESCRIPTION:
DSS Export Rating Curves= 0
DSS Export Rating Curve Sorted= 0
DSS Export Volume Flow Curves= 0
DXF OffsetX= 0
DXF OffsetY= 0
DXF ScaleX= 0
DXF ScaleY= 0

--- FALLSPRN.p01 (plan) ---

Plan Title=Floodplain
Program Version=6.20
Short Identifier=Floodplain
Geom File=g01
Flow File=f01
Subcritical Flow
K Sum by GR= 0
Std Step Tol= 0.01
Critical Tol= 0.01
Num of Std Step Trials= 20
Max Error Tol= 0.3
Flow Tol Ratio= 0.001
Split Flow NTrial= 30
Split Flow Tol= 0.02
Split Flow Ratio= 0.02
Log Output Level= 0
Friction Slope Method= 1
Unsteady Friction Slope Method= 2
Unsteady Bridges Friction Slope Method= 1
Parabolic Critical Depth
Global Vel Dist= 0 , 0 , 0
Global Log Level= 0
CheckData=True
Encroach Param=-1 ,0,0, 0
Mapping Interval=1HOUR
Computation Time Step Use Courant=        0
Computation Time Step Use Time Series=    0
Computation Time Step Count To Double=0
Computation Time Step Max Doubling=0
Computation Time Step Max Halving=0
Computation Time Step Residence Courant=0
Run HTab= 0
Run UNet= 0
Run Sediment= 0
Run PostProcess= 0
Run WQNet= 0
Run RASMapper=-1
UNET Theta= 0
UNET Theta Warmup= 0
UNET ZTol= 0
UNET ZSATol= 0
UNET MxIter= 0
UNET Max Iter WO Improvement= 0
UNET MaxInSteps= 0
UNET DtIC= 0
UNET DtMin= 0
UNET MaxCRTS= 0
UNET WFStab= 0
UNET SFStab= 0
UNET WFX= 1
UNET SFX= 1
UNET Gravity=32.174
UNET 1D Methodology=Finite Difference
UNET DSS MLevel= 1
UNET Pardiso=0
UNET DZMax Abort= 0
UNET Use Existing IB Tables= 0
UNET Froude Reduction=False
UNET Froude Limit= 0
UNET Froude Power= 0
UNET D1 Cores= 0
UNET WindReference=Eulerian
UNET WindDragFormulation=Hsu (1988)
UNET D2 Coriolis=0
UNET D2 Cores= 0
UNET D2 Theta= 1
UNET D2 Theta Warmup= 1
UNET D2 Z Tol= 0.01
UNET D2 Volume Tol= 0.01
UNET D2 Max Iterations= 20
UNET D2 Equation= 0
UNET D2 RampUpFraction=0.1
UNET D2 TimeSlices= 1
UNET D2 Turbulence Formulation=Non-Conservative (original)
UNET D2 Eddy Viscosity=0.3
UNET D2 Transverse Eddy Viscosity=0.1
UNET D2 Smagorinsky Mixing=0
UNET D2 BCVolumeCheck=0
UNET D2 Cores=0
UNET D2 SolverType=PARDISO (Direct)
UNET D2 Minimum Iterations= 2147483647
UNET D2 Maximum Iterations= 2147483647
UNET D2 Restart Number= 10
UNET D2 Relaxation Coeff=1.3
UNET D2 SOR Precondition Iterations= 10
UNET D2 ILUT Maximum Fill= 8
UNET D2 ILUT Tolerance=1E-08
UNET D1D2 MaxIter= 0
UNET D1D2 ZTol=0.01
UNET D1D2 QTol=0.1
UNET D1D2 MinQTol=1
Write IC File= 0
Write IC File at Fixed DateTime=0
Write IC File at Sim End=0
Echo Input=False
Echo Parameters=False
Echo Output=False
Write Detailed= 0
HDF Write Warmup=0
HDF Write Time Slices=0
HDF Flush=0
HDF Compression= 1
HDF Chunk Size= 1
HDF Spatial Parts= 1
HDF Use Max Rows=0
HDF Fixed Rows= 1
Calibration Method= 0
Calibration Iterations= 20
Calibration Max Change=0.05
Calibration Tolerance=0.2
Calibration Maximum=1.5
Calibration Minimum=0.5
Calibration Optimization Method= 1
WQ AD Non Conservative
WQ ULTIMATE=-1
WQ Max Comp Step=1HOUR
WQ Output Interval=15MIN
WQ Output Selected Increments= 0
WQ Output face flow=0
WQ Output face velocity=0
WQ Output face area=0
WQ Output face dispersion=0
WQ Output cell volume=0
WQ Output cell surface area=0
WQ Output cell continuity=0
WQ Output cumulative cell continuity=0
WQ Output face conc=0
WQ Output face dconc_dx=0
WQ Output face courant=0
WQ Output face peclet=0
WQ Output face adv mass=0
WQ Output face disp mass=0
WQ Output cell mass=0
WQ Output cell source sink temp=0
WQ Output nsm pathways=0
WQ Output nsm derived pathways=0
WQ Create Restart=0
WQ Fixed Restart=0
WQ System Summary=0
WQ Write To DSS=0
Sorting and Armoring Iterations= 10
XS Update Threshold= 0.02
Bed Roughness Predictor= 0
Hydraulics Update Threshold= 0.02
Energy Slope Method= 1
Volume Change Method= 1
Sediment Retention Method= 0
Sediment TS Multiplier= 1
Warm Up Method= 0
XS Weighting Method= 0
Number of US Weighted Cross Sections= 1
Number of DS Weighted Cross Sections= 1
Upstream XS Weight=0
Main XS Weight=1
Downstream XS Weight=0
Number of DS XS's Weighted with US Boundary= 1
Upstream Boundary Weight= 1
Weight of XSs Associated with US Boundary= 0
Number of US XS's Weighted with DS Boundary= 1
Downstream Boundary Weight= 0.5
Weight of XSs Associated with DS Boundary= 0.5
Percentile Method= 0
Sediment Output Level= 3
Mass or Volume Output= 0
Output Increment Type= 1
Profile and TS Output Increment= 1
Transport Output Increment 1
XS Output Flag= 0
XS Output Increment= 10
Read HDF5 Sediment Hotstart= 0
Sediment Hotstart Type= 0
Write Gradation File= 0
Read Gradation Hotstart= 0
Write HDF5 File= 1
Write Binary Output= 1
Write DSS Sediment File= 0
DSS Sediment Output Type= 1
SV Curve= 0
Specific Gage Flag= 0
Subcell Erosion Methods= 0
Subcell Deposition Methods= 0
Advection Scheme= 1
Matrix Solver= 0
Implicit Weighting Factor= 1
Maximum Outer Loop Convergence Iterations= 5
Convergence Maximum Absolute= 0.001
Convergence RMSE= 0.0001
Grain Fractions Max Abs Error= 0.001
Max Subgrid Regions= 1
Max Subgrid Length Scale= 3.402823E+38
Initial Layer Thickness= 3.402823E+38
Min Layer Thickness= 3.402823E+38
Max Layer Thickness= 3.402823E+38
Number of Layers= 5

--- FALLSPRN.f01 (steady flow) ---

Flow Title=Flow
Program Version=6.20
Number of Profiles= 1
Profile Names=P100yr
River Rch & RM=FALLSPRN,Main            ,6122
     444
River Rch & RM=FALLSPRN,Main            ,3843
     545
River Rch & RM=FALLSPRN,Main            ,3328
     608
Boundary for River Rch & Prof#=FALLSPRN,Main            , 1
Up Type= 0
Dn Type= 3
Dn Slope=0.11727
DSS Import GetInterval= 0
DSS Import GetPeak= 0
DSS Import FillOption= 0

--- FALLSPRN.g01 (geometry) ---

Geom Title=Geometry
Program Version=6.20

River Reach=FALLSPRN        ,Main
Reach XY= 30
2226361.45416787 542836.630351252226257.18953142542845.656894417
     2226146.857      542762.466     2226122.648      542708.645
     2226061.793      542684.609     2225744.187      542763.766
     2225163.457      542659.078     2224969.707      542574.703
     2224779.083      542442.412     2224532.771      542379.473
     2224198.197      542422.799     2224113.591      542384.945
     2223996.678      542224.941     2223922.622      542184.327
     2223671.381      542165.148     2223515.097      542190.213
     2223356.472      542124.655     2223220.306      542116.254
     2223109.485      542020.105     2222845.317      542076.803
2222775.94255199542063.5209960852222736.62181286542039.659033428
 2222731.8352055541995.977047396     2222514.907      541830.464
     2222473.799      541750.625      2222136.87      541493.178
     2221979.581      541458.025     2221392.081       541410.63
     2221189.477      541314.796     2220946.097      541121.735

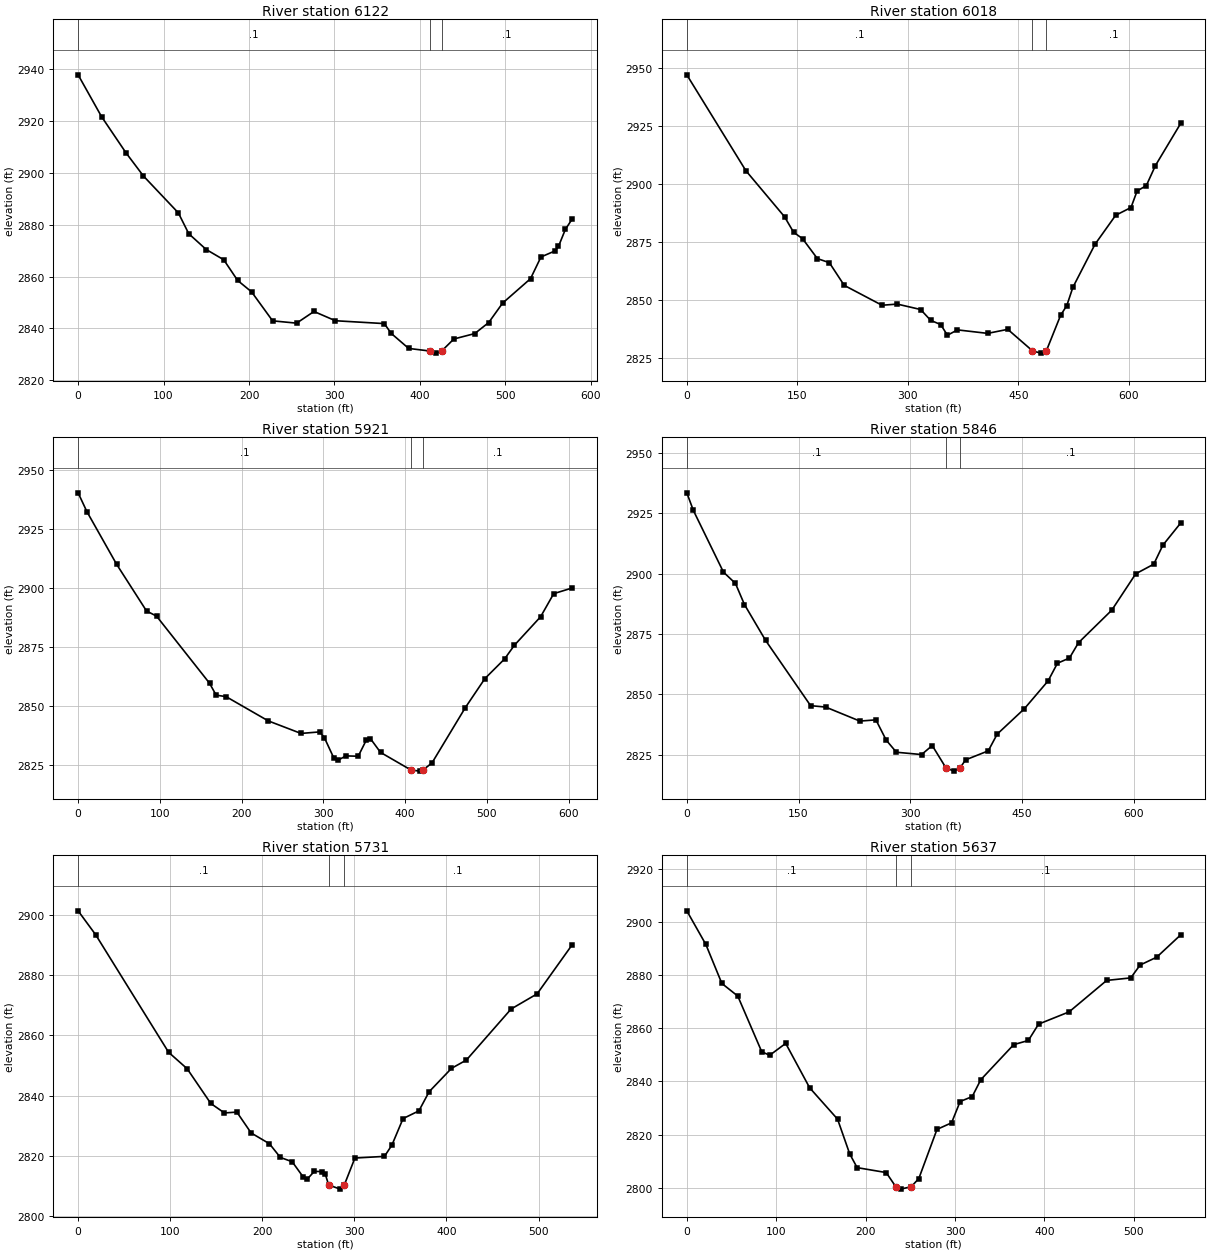
Type RM Length L Ch R = 1 ,6122    ,97.9,103.3,110.2
XS GIS Cut Line= 4
2226427.63512893542426.3526104832226351.23669753 542795.30113284
2226365.21202035542872.6312524252226340.98812746542992.819028647
#Sta/Elev= 30
       0 2937.72    27.4 2921.62      56 2907.68    76.4 2898.75   117.3 2884.52
   129.5 2876.48   149.9 2870.41   170.4 2866.46   186.7 2858.48     203 2854.08
   227.6 2842.92   255.7 2842.03     276 2846.53   301.1 2842.96   358.3 2841.86
   366.4 2838.08   386.8 2832.29   411.2 2831.31   419.3 2830.48  425.51 2831.32
   439.7 2835.93   464.1 2838.01   480.5 2842.28   496.7 2849.74   529.4 2859.17
   541.6 2867.53   557.9 2869.85   562.1 2871.58   570.2 2878.18577.9629 2882.06
#Mann= 3, -1 ,  0
       0     0.1       0   411.2   0.045       0  425.51     0.1       0
Bank Sta=411.2,425.51
XS Rating Curve= 0 ,0
Exp/Cntr(USF)=0,0
Exp/Cntr=0.3,0.1

Type RM Length L Ch R = 1 ,6018    ,96.6,97.8,99.5
XS GIS Cut Line= 4
 2226411.7674314 542401.82309693 2226378.8956397542620.790610331
2226247.46144352 542863.400504272226200.93773968543030.143099923
#Sta/Elev= 30
       0 2947.26    80.2 2905.81   132.7 2885.89     145 2879.18   157.1 2876.43
   177.3  2867.8   193.5 2866.05   213.7 2856.24     265 2847.64   285.7 2848.14
   317.4  2845.8     331 2841.12   344.7 2839.28   353.8 2834.66   367.4 2836.99
   408.4 2835.48   435.7 2837.22  469.19 2827.95   480.4 2826.94  488.13 2827.95
   507.5 2843.34   515.8 2847.46   524.1 2855.38   554.2 2874.02   582.2 2886.54
     603 2889.89   611.3 2897.05   623.8 2899.37   636.2 2908.05   670.5 2926.28
#Mann= 3, -1 ,  0
       0     0.1       0  469.19   0.045       0  488.13     0.1       0
Bank Sta=469.19,488.13
XS Rating Curve= 0 ,0
Exp/Cntr=0.3,0.1

Type RM Length L Ch R = 1 ,5921    ,71.9,74.6,76.5
XS GIS Cut Line= 4
 2226342.3489566542418.5736890652226310.74911777542611.332705929
2226165.38985915542805.1450507542226162.22987527542971.570868593
#Sta/Elev= 30
       0 2940.36    10.7 2932.43    47.2 2910.06    83.7 2890.36    95.9  2888.2
   160.7 2859.82   168.8 2854.77     181 2854.12   232.6 2843.86   272.6 2838.56
   295.6 2839.21   301.3 2836.69   312.6 2828.27   317.6 2827.19   327.6 2829.06
   342.6 2828.91   352.6 2835.82   357.6 2836.32   369.9 2830.53   407.1 2823.09
   417.6 2822.61  421.862823.106   432.8 2826.07   473.6 2849.48   497.6 2861.79
   521.6 2870.07   533.6 2875.87   565.7 2887.94   581.7  2897.7   604.1 2900.08
#Mann= 3, -1 ,  0
       0     0.1       0   407.1   0.045       0  421.86     0.1       0
Bank Sta=407.1,421.86
XS Rating Curve= 0 ,0
Exp/Cntr(USF)=0,0
Exp/Cntr=0.3,0.1

Type RM Length L Ch R = 1 ,5846    ,125.4,115.2,108.2
XS GIS Cut Line= 4
2226273.59526539 542428.433790272226243.79436032542653.515176832
2226099.97018103 542756.575270812226137.47501894543012.987137939
#Sta/Elev= 30
       0  2933.5     8.8  2926.2    49.2 2900.63    65.3 2895.94    77.4 2887.18
   105.7 2872.35   166.2 2845.26   186.4 2844.68   232.3 2838.87   253.9 2839.37
   267.7 2830.97   281.4 2825.95   315.2 2824.99   329.5 2828.73  347.792819.525
   358.4 2818.12     367 2819.52   374.2 2822.78   404.7 2826.52   416.7 2833.46
   453.1 2843.96     485 2855.51   497.6 2862.85   513.7    2865   525.9 2871.37
   570.5 2884.84   602.7 2899.93   626.9 2903.92   639.1 2911.78   663.1    2921
#Mann= 3, -1 ,  0
       0     0.1       0  347.79   0.045       0     367     0.1       0
Bank Sta=347.79,367
XS Rating Curve= 0 ,0
Exp/Cntr(USF)=0,0
Exp/Cntr=0.3,0.1

Type RM Length L Ch R = 1 ,5731    ,94.5,93.9,92.5
XS GIS Cut Line= 4
2226162.22987527542441.7469042072226036.88384791 542612.38603389
2226040.04383179542721.9321418352226071.64367062542934.704389958
#Sta/Elev= 30
       0 2901.29    19.1 2893.34    98.3 2854.37   118.4 2848.93   144.1 2837.41
   158.9 2834.26   172.4 2834.55   187.9 2827.63   207.8 2824.05   219.6 2819.52
   232.5 2818.08   244.5 2813.01   248.5  2812.2   256.5 2814.89   264.5 2814.82
   268.5 2813.89   272.12810.381   284.6    2809  289.072810.358   300.6 2819.31
   332.7 2819.86   340.8 2823.61   352.9  2832.4   370.1 2834.95   381.2 2841.29
   405.5 2849.05   421.7 2851.81   470.2 2868.72   498.5 2873.76   536.4 2889.97
#Mann= 3, -1 ,  0
       0     0.1       0   272.1   0.045       0  289.07     0.1       0
Bank Sta=272.1,289.07
XS Rating Curve= 0 ,0
Exp/Cntr(USF)=0,0
Exp/Cntr=0.3,0.1

Type RM Length L Ch R = 1 ,5637    ,147.7,147.1,146.3
XS GIS Cut Line= 5
2225859.05263304542478.0895732772225941.56891247542644.544854644
2225957.12757598542735.5619006462225987.03367397 542876.84533861
2226053.99741261542988.100612581
#Sta/Elev= 30
       0 2904.25    21.3 2891.59    39.2 2876.91      57 2872.16    83.8  2851.2
    92.7 2849.87   110.6 2854.34   137.4 2837.62   168.6 2825.82   182.2 2812.73
   190.5 2807.56     223 2805.71   233.72800.395   239.2 2799.47     251 2800.38
   259.5 2803.47   279.8 2821.96   296.1 2824.43   305.7 2832.46   319.2 2834.31
   328.8 2840.67   365.6 2853.87     382 2855.44   393.4 2861.59   427.6 2866.21
   469.6 2878.05   496.5    2879     507 2883.84   525.6 2886.81   552.4 2895.21
#Mann= 3, -1 ,  0
       0     0.1       0   233.7   0.045       0     251     0.1       0
Bank Sta=233.7,251
XS Rating Curve= 0 ,0
Exp/Cntr=0.3,0.1

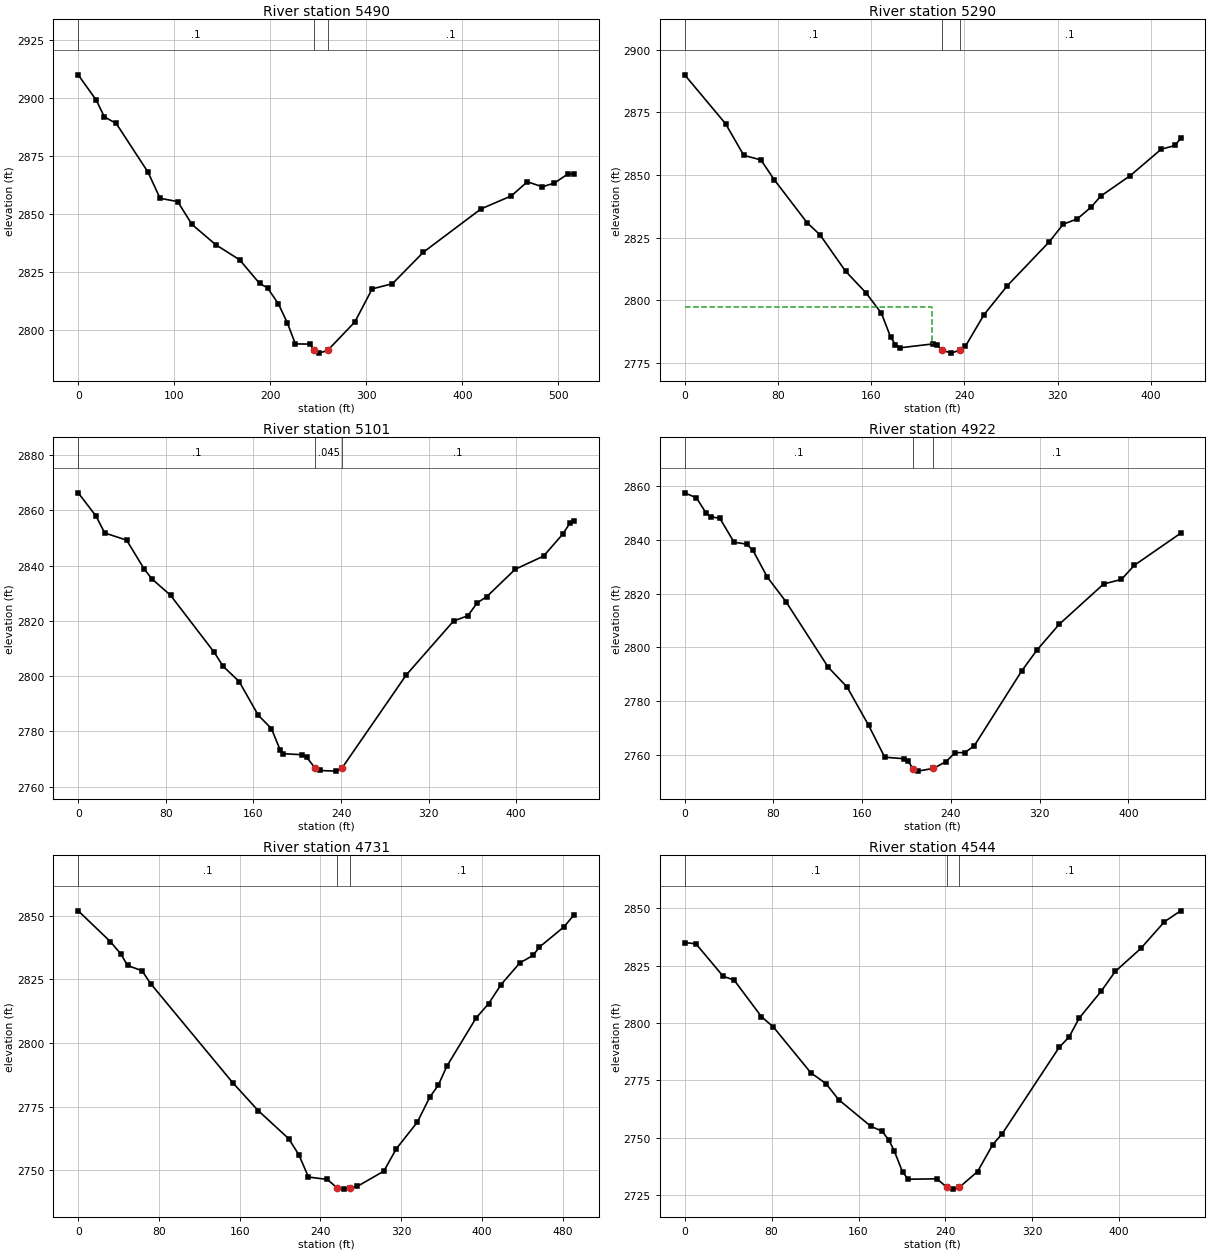
Type RM Length L Ch R = 1 ,5490    ,197.9,200,201.3
XS GIS Cut Line= 4
2225742.80038185542490.9273243772225801.20598151542706.497083142
 2225820.2750126542781.5755170492225964.71923108542941.690846054
#Sta/Elev= 30
       0 2910.09    18.9 2899.11    27.2    2892    39.6 2889.14    72.8 2868.09
    85.2 2856.93   103.6  2855.5   118.4 2845.69   143.2 2836.93   168.1 2830.43
   188.8 2820.28   197.1 2818.36   208.4  2811.5   217.8 2803.26   226.1 2794.22
   241.2 2794.14  245.772791.589   250.9 2790.25  259.732791.437     288 2803.65
   306.1 2817.91   327.2 2820.15   359.5 2833.74   419.4 2852.35   451.1 2857.98
   467.6 2864.04   483.4 2861.87   495.9 2863.52   509.7 2867.34   516.4 2867.39
#Mann= 3, -1 ,  0
       0     0.1       0  245.77   0.045       0  259.73     0.1       0
Bank Sta=245.77,259.73
XS Rating Curve= 0 ,0
Exp/Cntr(USF)=0,0
Exp/Cntr=0.3,0.1

Type RM Length L Ch R = 1 ,5290    ,188.4,188.7,188.9
XS GIS Cut Line= 4
2225691.86063576542518.7070445632225623.04822015 542676.40216366
2225621.43514245542790.5230630212225621.82899795542929.818793485
#Sta/Elev= 30
       0 2889.92    35.1  2870.4    50.7 2857.81    65.4 2855.98    76.9 2848.05
   104.9 2831.02   116.2 2826.06     138 2811.62   155.4 2803.05   168.8 2794.83
   176.8 2785.18   180.8 2782.34   184.8 2781.06   212.8 2782.59   216.8 2781.99
   220.8 2780.12   228.8 2778.93  235.862780.135   240.8 2781.63   256.8 2794.24
   276.8 2805.81   312.8 2823.32   324.8 2830.34   336.8 2832.46   348.8 2837.18
   356.8 2841.49   382.4 2849.76   408.8 2860.23   420.8 2861.75   425.5 2864.69
#Mann= 3, -1 ,  0
       0     0.1       0   220.8   0.045       0  235.86     0.1       0
#XS Ineff= 2 , 0
          211.91 2797.41
Permanent Ineff=
       F       F
Bank Sta=220.8,235.86
XS Rating Curve= 0 ,0
Exp/Cntr(USF)=0,0
Exp/Cntr=0.3,0.1

Type RM Length L Ch R = 1 ,5101    ,177,179.5,182.7
XS GIS Cut Line= 4
2225447.93237698542480.9801715192225440.55578484542650.831109854
2225432.78694409542743.1046186882225505.49569656542918.909890172
#Sta/Elev= 30
       0  2866.3    16.2 2857.93    24.2 2851.78    44.2 2849.17    60.3 2838.71
    67.4 2835.12    84.3 2829.23   124.3 2808.53   132.3 2803.55     147    2798
   164.4 2785.83   176.4    2781   184.4 2773.27   187.3 2771.89   204.5 2771.52
   208.5 2770.66     216 2766.87   220.5 2765.82   235.5 2765.59  241.132766.836
   299.5 2800.36   342.8 2819.92   355.8 2821.82   364.4 2826.49   373.1 2828.73
     399 2838.62     425 2843.42   442.3 2851.27   449.4 2855.53   452.9 2856.24
#Mann= 3, -1 ,  0
       0     0.1       0     216   0.045       0  241.13     0.1       0
Bank Sta=216,241.13
XS Rating Curve= 0 ,0
Exp/Cntr=0.3,0.1

Type RM Length L Ch R = 1 ,4922    ,190,190.9,190.6
XS GIS Cut Line= 4
2225333.41895965542467.2329538912225276.28745159542628.176592442
2225245.63152044542715.2673059432225227.61318056542898.307375727
#Sta/Elev= 30
       0 2857.37    10.6 2855.52      19 2850.05    23.3 2848.55    31.8 2847.86
    44.5 2839.02    55.8 2838.34    61.5 2836.02    74.5 2826.07    91.2 2817.02
   129.4 2792.63   146.4 2785.26   165.7 2771.14   180.3 2759.24   197.3 2758.68
   201.5 2757.76   205.8 2754.94     210 2754.07   224.12755.073   235.5 2757.59
   243.9 2760.95   252.4 2760.93   260.9  2763.4   303.7 2791.21   317.4 2798.95
   337.4  2808.5   377.6 2823.53   393.7 2825.23   405.2 2830.44     447 2842.37
#Mann= 3, -1 ,  0
       0     0.1       0   205.8   0.045       0   224.1     0.1       0
Bank Sta=205.8,224.1
XS Rating Curve= 0 ,0
Exp/Cntr(USF)=0,0
Exp/Cntr=0.3,0.1

Type RM Length L Ch R = 1 ,4731    ,184.4,186.9,189.4
XS GIS Cut Line= 4
2225231.37910396542411.7929306072225094.71000074542589.558337589
2225062.21524893542661.2379371792225011.56166522 542842.82625614
#Sta/Elev= 30
       0 2851.92    31.8 2839.84    42.1 2835.03    48.9 2830.43    63.2 2828.39
    71.7 2823.35   153.1 2784.37   178.3 2773.41   208.7 2762.31   218.7 2755.98
   228.2 2747.27     247 2746.32   256.1 2743.13   263.3 2742.52   269.1 2743.14
   276.5 2743.57   302.9  2749.6   315.3 2758.41   336.1 2768.85   348.5 2778.75
   356.9 2783.38   365.2 2790.75   394.2 2809.73   406.7 2815.42   419.1 2822.95
   437.7 2831.46   450.7 2834.37   457.1 2837.67   481.4 2845.61   491.5  2850.4
#Mann= 3, -1 ,  0
       0     0.1       0   256.1   0.045       0   269.1     0.1       0
Bank Sta=256.1,269.1
XS Rating Curve= 0 ,0
Exp/Cntr(USF)=0,0
Exp/Cntr=0.3,0.1

Type RM Length L Ch R = 1 ,4544    ,158.3,156.5,153.5
XS GIS Cut Line= 4
2225074.62376517542345.0575611152224954.52233033542501.656102209
2224898.42060393542550.2399488472224821.96321838542718.599147567
#Sta/Elev= 30
       0 2835.05    10.4 2834.47    35.4 2820.34    45.5 2818.66    70.7 2802.69
    81.7 2798.16   116.1 2778.24   130.2 2773.45   141.6 2766.56   171.5 2754.83
   181.6 2752.81   188.1 2748.77     193 2744.06   200.5    2735   205.7  2731.8
   232.2 2731.97   241.2 2728.33   246.9 2727.48252.69842728.227   269.6 2735.14
   283.6 2746.93   292.4 2751.72   344.7 2789.31   353.9  2793.9   363.1 2802.05
   383.4 2813.82   396.3 2822.42   419.8 2832.45   441.6 2844.12   456.5 2848.88
#Mann= 3, -1 ,  0
       0     0.1       0   241.2   0.045       0252.6984     0.1       0
Bank Sta=241.2,252.6984
XS Rating Curve= 0 ,0
Exp/Cntr=0.3,0.1

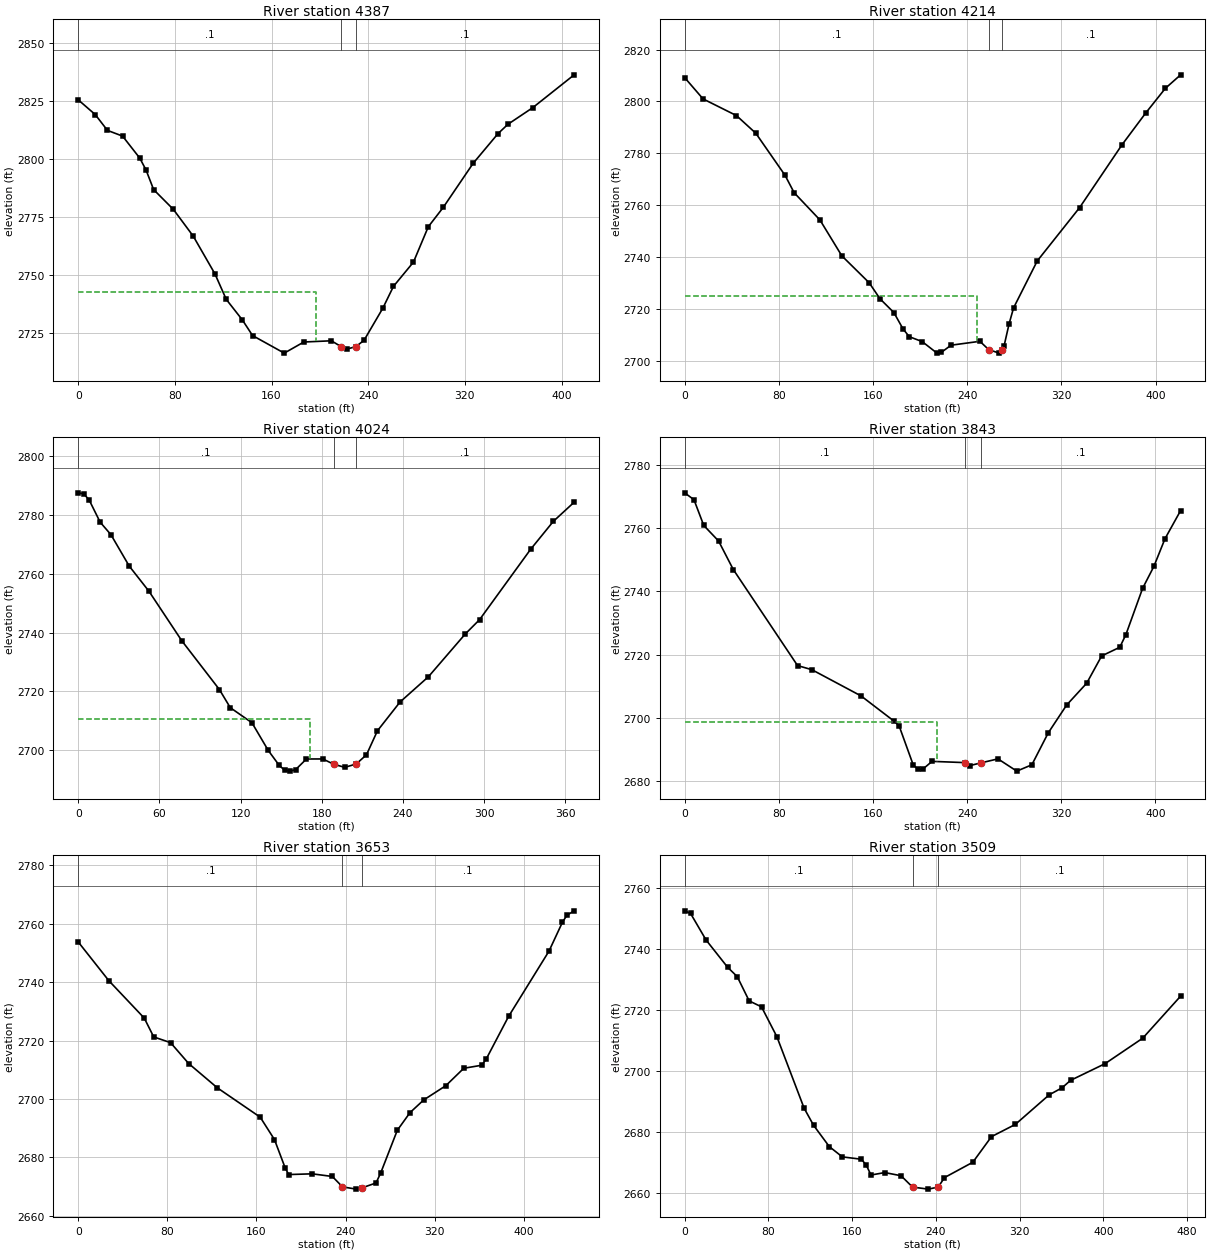
Type RM Length L Ch R = 1 ,4387    ,174.2,173.5,171.4
XS GIS Cut Line= 4
2224922.34736031542275.4331085552224814.97544981542391.064396782
2224777.25569765542470.1932471382224737.81492716542630.388125901
#Sta/Elev= 30
       0 2825.63    14.1 2819.25    24.2 2812.42    36.7 2809.96    50.9 2800.48
    56.1 2795.36    62.4 2786.86    78.8 2778.27    95.2 2766.74   113.2  2750.4
   122.5 2739.45   135.8 2730.59   144.3 2723.81   170.5 2716.23   186.7 2721.03
   209.5 2721.56   217.7 2718.99   222.2 2717.96  229.732719.035   236.5 2721.74
   252.1 2735.66   260.9 2745.09   277.4 2755.52   289.7 2770.81   302.1 2779.19
   326.8 2798.19   347.4 2811.03   355.6 2815.06   376.2 2822.26   410.4 2836.42
#Mann= 3, -1 ,  0
       0     0.1       0   217.7   0.045       0  229.73     0.1       0
#XS Ineff= 2 , 0
          197.11 2742.48
Permanent Ineff=
       F       F
Bank Sta=217.7,229.73
XS Rating Curve= 0 ,0
Exp/Cntr(USF)=0,0
Exp/Cntr=0.3,0.1

Type RM Length L Ch R = 1 ,4214    ,192.6,189.5,187.5
XS GIS Cut Line= 5
2224783.28794368542230.3774513622224680.49999962542257.897261393
2224637.10511104542331.1639594092224618.82882251542418.574537826
2224616.86434553542558.949603508
#Sta/Elev= 30
       0 2809.19    15.6 2800.98      44 2794.54    60.4 2787.74    85.3 2771.47
      93 2764.78   114.9 2754.28   133.5 2740.43   156.7 2730.05     166 2723.82
   177.7 2718.55   185.5 2712.22   190.8 2709.23   201.8 2707.33   214.1 2702.97
   218.1 2703.21   226.3 2705.95   250.8 2707.45   258.3 2704.23   267.2 2702.89
  269.312704.239   271.3 2705.63   275.6 2714.22   279.4 2720.35   299.5 2738.46
   335.5 2759.04   371.5 2783.28   391.5 2795.45   408.3 2805.04   421.3 2810.27
#Mann= 3, -1 ,  0
       0     0.1       0   258.3   0.045       0  269.31     0.1       0
#XS Ineff= 2 , 0
          248.01 2725.03
Permanent Ineff=
       F       F
Bank Sta=258.3,269.31
XS Rating Curve= 0 ,0
Exp/Cntr(USF)=0,0
Exp/Cntr=0.3,0.1

Type RM Length L Ch R = 1 ,4024    ,182,181.3,183
XS GIS Cut Line= 4
2224419.33725727542180.9781499182224427.13781301542309.948289541
2224438.57033436542400.8025996162224482.44031461542539.884993993
#Sta/Elev= 30
       0 2787.53     4.2 2787.18     8.2    2785    16.2 2777.56    24.2 2773.29
    37.7 2762.62    52.3 2754.05    76.6 2737.19   104.4  2720.6   112.4 2714.46
   128.4 2709.34   140.5 2699.89   148.6 2694.82   152.6 2693.17   156.7 2692.87
   160.7 2693.38   168.7    2697   180.8 2697.01   188.9 2695.21     197 2694.16
   205.5 2695.29   213.1 2698.44   221.2  2706.6   237.9 2716.38   258.9 2724.99
   286.1 2739.51   296.7  2744.4   334.4 2768.31   351.2 2777.82   366.6 2784.34
#Mann= 3, -1 ,  0
       0     0.1       0   188.9   0.045       0   205.5     0.1       0
#XS Ineff= 2 , 0
          171.26 2710.62
Permanent Ineff=
       F       F
Bank Sta=188.9,205.5
XS Rating Curve= 0 ,0
Exp/Cntr=0.3,0.1

Type RM Length L Ch R = 1 ,3843    ,184.6,190.4,197.2
XS GIS Cut Line= 4
2224308.04321378542193.6275027682224262.99307604542344.035842617
2224264.38652746542481.5996771452224195.93155412542588.376475879
#Sta/Elev= 30
       0 2771.19     7.9 2769.01    16.2 2760.87    28.8 2755.94    41.3 2746.91
    95.9  2716.5   108.1 2715.19   149.9 2706.88   178.2 2698.82   182.2 2697.41
   194.2 2685.04   198.2 2683.66   202.2 2683.66   210.2 2686.17   237.8 2685.78
   242.5 2684.85  251.83  2685.7   266.2 2686.96   282.2 2683.08     295 2685.09
   308.9 2695.18   324.6 2704.03   341.6 2710.92   354.3 2719.55   369.7 2722.29
   374.9  2726.3   389.1 2740.95   398.7 2747.91   408.1 2756.64   421.4 2765.57
#Mann= 3, -1 ,  0
       0     0.1       0   237.8   0.045       0  251.83     0.1       0
#XS Ineff= 2 , 0
          214.08 2698.79
Permanent Ineff=
       F       F
Bank Sta=237.8,251.83
XS Rating Curve= 0 ,0
Exp/Cntr(USF)=0,0
Exp/Cntr=0.3,0.1

Type RM Length L Ch R = 1 ,3653    ,140.9,143.7,145.7
XS GIS Cut Line= 4
2224249.33986197542175.2966643342224148.73664379542307.108974698
 2224058.2858404542395.7684979612224041.68809431542547.647917331
#Sta/Elev= 30
       0 2753.77    27.5  2740.5    59.3 2727.69    67.8 2721.24    82.9 2719.29
    99.2 2712.13   124.9 2703.82   163.4 2693.77   176.2 2686.11   185.9 2676.32
     189 2674.12   210.1 2674.37   228.2 2673.46   237.3  2669.9   249.7 2669.13
   254.5 2669.53   267.4 2671.24   271.6 2674.66   286.5 2689.27   297.9 2695.32
   310.2 2699.66   330.1 2704.56   346.2 2710.51   362.3 2711.55   366.3 2713.64
   386.4 2728.25   422.7 2750.62   434.7 2760.45   438.8 2762.91   445.3 2764.42
#Mann= 3, -1 ,  0
       0     0.1       0   237.3   0.045       0   254.5     0.1       0
Bank Sta=237.3,254.5
XS Rating Curve= 0 ,0
Exp/Cntr=0.3,0.1

Type RM Length L Ch R = 1 ,3509    ,196.3,180.6,171.6
XS GIS Cut Line= 3
2224220.11801322542129.4615329532223990.97266925542255.646300071
2223955.67869633542464.920997115
#Sta/Elev= 30
       0 2752.62     5.6 2751.77    20.4 2743.05      41 2734.08    50.2    2731
    61.6 2723.02    73.4 2721.06    88.1 2711.24   114.1 2687.75   123.2  2682.1
   138.2 2675.12   150.6 2671.75   168.9 2670.97   173.5 2669.01     178 2665.79
   191.2 2666.59   206.7 2665.55   217.7 2661.82   232.8 2661.15  242.262661.842
   248.2 2664.94   275.3 2669.99   293.1  2678.4   315.9 2682.42   348.3 2692.16
   360.5 2694.44   368.6 2696.89   401.6 2702.38   437.6 2710.76   473.8 2724.58
#Mann= 3, -1 ,  0
       0     0.1       0   217.7   0.045       0  242.26     0.1       0
Bank Sta=217.7,242.26
XS Rating Curve= 0 ,0
Exp/Cntr(USF)=0,0
Exp/Cntr=0.3,0.1

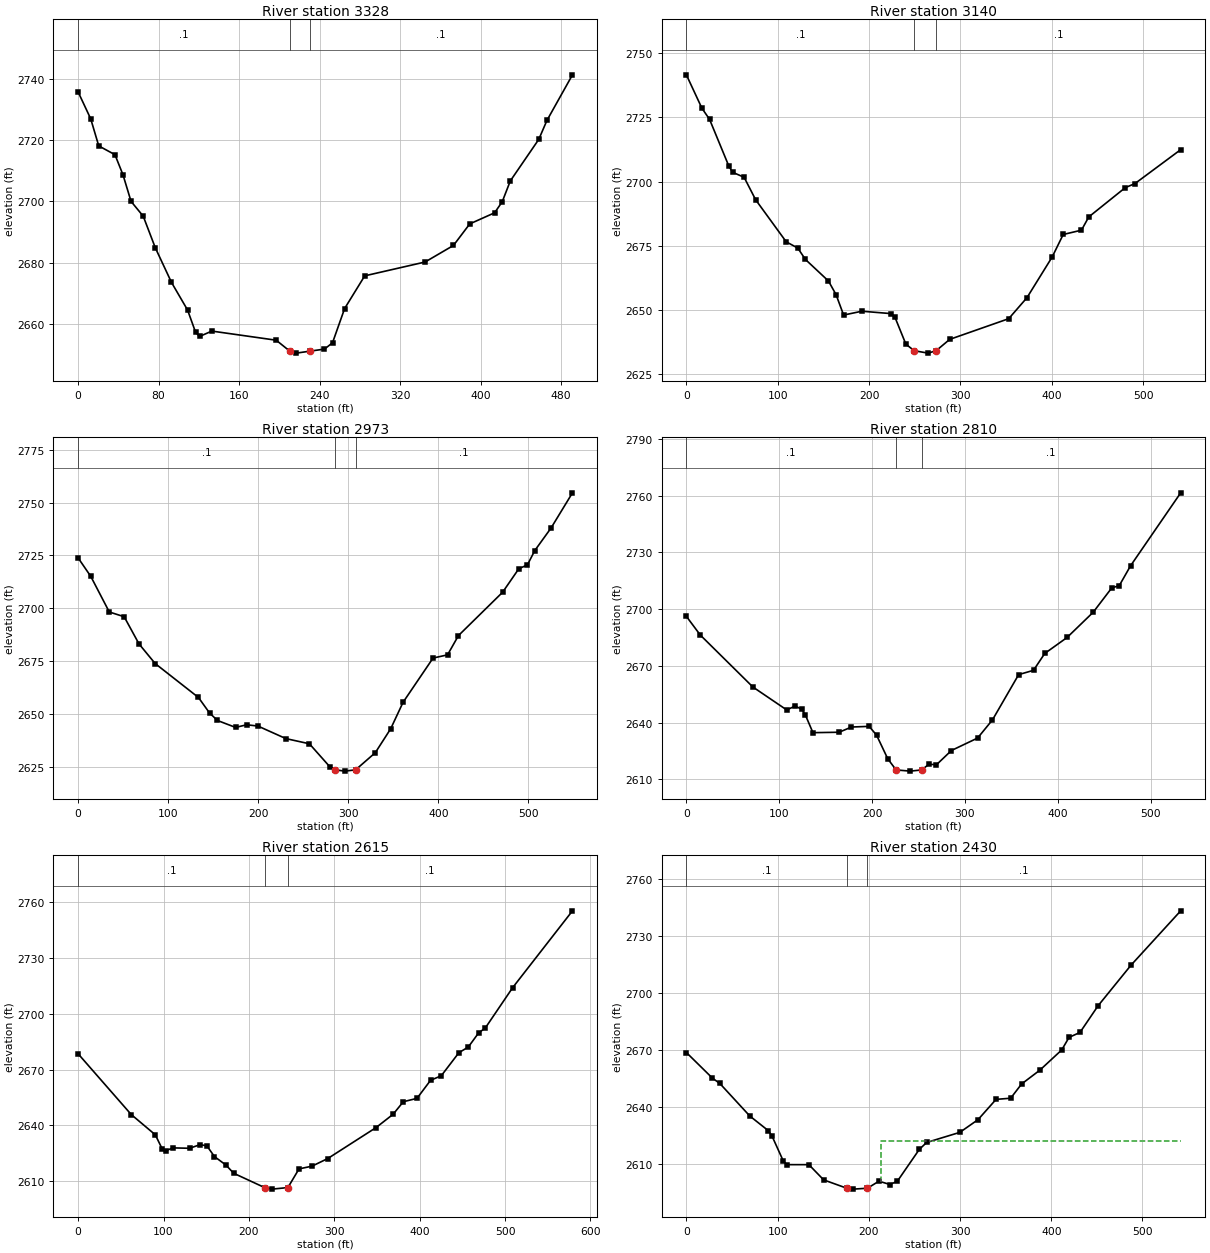
Type RM Length L Ch R = 1 ,3328    ,188.3,187.9,186.8
XS GIS Cut Line= 4
2223861.45123871 541968.722893992223852.01076996542081.849230943
2223854.17333431542310.9645845282223834.39047763542458.376455344
#Sta/Elev= 30
       0 2735.87    12.5 2727.07    20.5  2718.2    36.6 2715.33    44.6 2708.73
    52.6 2700.03    64.7 2695.19    76.7 2684.85    92.8  2673.5   108.8 2664.45
   116.8 2657.12   120.8 2655.81   132.9 2657.56   196.9 2654.57  210.422650.989
   216.9 2650.34  230.51 2650.99   244.9 2651.66   252.9 2653.75   264.9 2664.94
   284.9 2675.65   344.9 2680.18   373.1 2685.61   389.3 2692.66     414  2696.3
   421.6 2699.93   429.6 2706.73   457.9 2720.34     466 2726.53   491.4 2741.48
#Mann= 3, -1 ,  0
       0     0.1       0  210.42   0.045       0  230.51     0.1       0
Bank Sta=210.42,230.51
XS Rating Curve= 0 ,0
Exp/Cntr(USF)=0,0
Exp/Cntr=0.3,0.1

Type RM Length L Ch R = 1 ,3140    ,159.1,167.3,169.7
XS GIS Cut Line= 4
2223714.53429705541916.9419498492223663.44107846542078.689355644
 2223673.9540864542310.9312583172223679.90535408542449.692300223
#Sta/Elev= 30
       0 2741.61      17  2728.6    25.4 2724.24    46.4  2706.1    50.6 2703.62
    63.2 2701.67    75.8 2692.91   109.3  2676.5   121.9 2674.08   130.3 2669.63
   155.5 2661.23   163.8 2655.93   172.1 2647.95   192.1 2649.45   224.2 2648.51
   228.2 2647.17   240.2 2636.63   249.3 2634.05   264.6 2633.11  273.362634.055
   288.2 2638.47   352.8 2646.54   372.8 2654.75   400.4 2670.63   412.4 2679.36
   432.4 2681.05   440.4 2686.21   480.4 2697.64   490.9  2699.2     541 2712.44
#Mann= 3, -1 ,  0
       0     0.1       0   249.3   0.045       0  273.36     0.1       0
Bank Sta=249.3,273.36
XS Rating Curve= 0 ,0
Exp/Cntr(USF)=0,0
Exp/Cntr=0.3,0.1

Type RM Length L Ch R = 1 ,2973    ,167.6,163.4,159.7
XS GIS Cut Line= 4
 2223590.3896591541899.6314159032223537.09179079542111.844083671
2223473.28040702 542252.780076062223451.10652498542426.769730726
#Sta/Elev= 30
       0 2723.78      14 2715.07    34.6 2698.18    51.1 2695.94    67.6 2683.06
    85.5 2673.78   133.6  2657.7   145.9 2650.38   154.7 2646.81   174.8 2643.53
   187.2 2644.77   199.6 2644.18   230.7 2638.23   256.8 2635.78   279.2 2625.02
  285.342623.441   296.1 2622.83   308.1 2623.44     330 2631.57   347.1 2642.92
   360.8 2655.42   394.1 2676.37   410.2 2677.88   422.3 2687.01   471.4 2707.56
   489.3 2718.64   498.9  2720.5     507 2727.23   525.1 2737.93   548.9  2754.6
#Mann= 3, -1 ,  0
       0     0.1       0  285.34   0.045       0   308.1     0.1       0
Bank Sta=285.34,308.1
XS Rating Curve= 0 ,0
Exp/Cntr(USF)=0,0
Exp/Cntr=0.3,0.1

Type RM Length L Ch R = 1 ,2810    ,170.1,194.6,197.3
XS GIS Cut Line= 4
2223386.23899411541886.3060719582223366.57380903542020.029330453
2223348.30225252542168.6780959372223325.03946159542414.929547585
#Sta/Elev= 30
       0 2696.15      15 2686.27    71.6 2658.81     108 2646.69   117.1  2648.7
   124.2 2647.06   128.2 2643.95   136.3 2634.65   164.5 2634.88   177.8 2637.64
   196.8 2637.98   204.8 2633.35   216.9  2620.8  225.852614.954   241.1 2614.32
   253.2 2614.94   261.3 2617.96   269.3 2617.69   285.4 2625.22   313.6 2631.81
   329.6  2641.4   357.8 2665.34   373.8 2667.62   385.9 2676.53     410    2685
   438.1 2698.34     458 2711.15   466.2 2712.43   478.3 2722.88   532.3 2761.46
#Mann= 3, -1 ,  0
       0     0.1       0  225.85   0.045       0   253.2     0.1       0
Bank Sta=225.85,253.2
XS Rating Curve= 0 ,0
Exp/Cntr(USF)=0,0
Exp/Cntr=0.3,0.1

Type RM Length L Ch R = 1 ,2615    ,210,185.5,179.2
XS GIS Cut Line= 4
2223271.47194528541891.2984660322223255.21501209 542042.25570277
2223153.53603623542094.476849174 2223142.3447119542407.119839509
#Sta/Elev= 30
       0 2678.48    62.2 2645.87    90.4 2634.98    98.4 2627.47   102.5 2626.41
   111.1 2627.96   130.6 2627.75   142.7 2629.68   150.7  2629.1   159.7 2623.28
   173.2 2618.71   182.2 2614.33   218.6 2606.61   227.2 2605.81  245.712606.651
   258.7 2616.67   273.9 2618.14   292.4 2622.24   348.9 2638.85   368.9    2646
   380.9 2652.75   396.9 2654.56   412.8 2664.26   425.3 2666.68     446 2679.09
     457 2682.13     469 2689.65     477 2692.41     509 2714.05     579 2755.27
#Mann= 3, -1 ,  0
       0     0.1       0   218.6   0.045       0  245.71     0.1       0
Bank Sta=218.6,245.71
XS Rating Curve= 0 ,0
Exp/Cntr(USF)=0,0
Exp/Cntr=0.3,0.1

Type RM Length L Ch R = 1 ,2430    ,191.7,191.3,192.7
XS GIS Cut Line= 4
2223025.26422232541853.3171949832223007.45900978541933.053581567
2223030.25312245542095.6229134392223038.89913083542391.573932652
#Sta/Elev= 30
       0 2668.81    28.5 2655.38    36.7 2652.54    69.5 2635.47    89.9 2627.73
    93.9 2624.91   106.1 2611.99   110.1 2609.91   134.3  2609.9   150.5 2601.91
  175.872597.521   182.8 2597.05   198.5 2597.52   211.1 2601.22   223.2 2599.48
   231.3  2601.2   255.4 2617.95   263.4 2621.55   299.8 2626.87   319.7 2633.53
   339.5 2644.19   355.5  2644.8   367.5 2652.28   387.5 2659.53   411.5 2670.17
   419.5 2676.75   431.5 2679.35   451.4  2693.4   487.5 2714.71   541.9 2743.22
#Mann= 3, -1 ,  0
       0     0.1       0  175.87   0.045       0   198.5     0.1       0
#XS Ineff= 2 , 0
                          213.14         2622.52
Permanent Ineff=
       F       F
Bank Sta=175.87,198.5
XS Rating Curve= 0 ,0
Exp/Cntr(USF)=0,0
Exp/Cntr=0.3,0.1

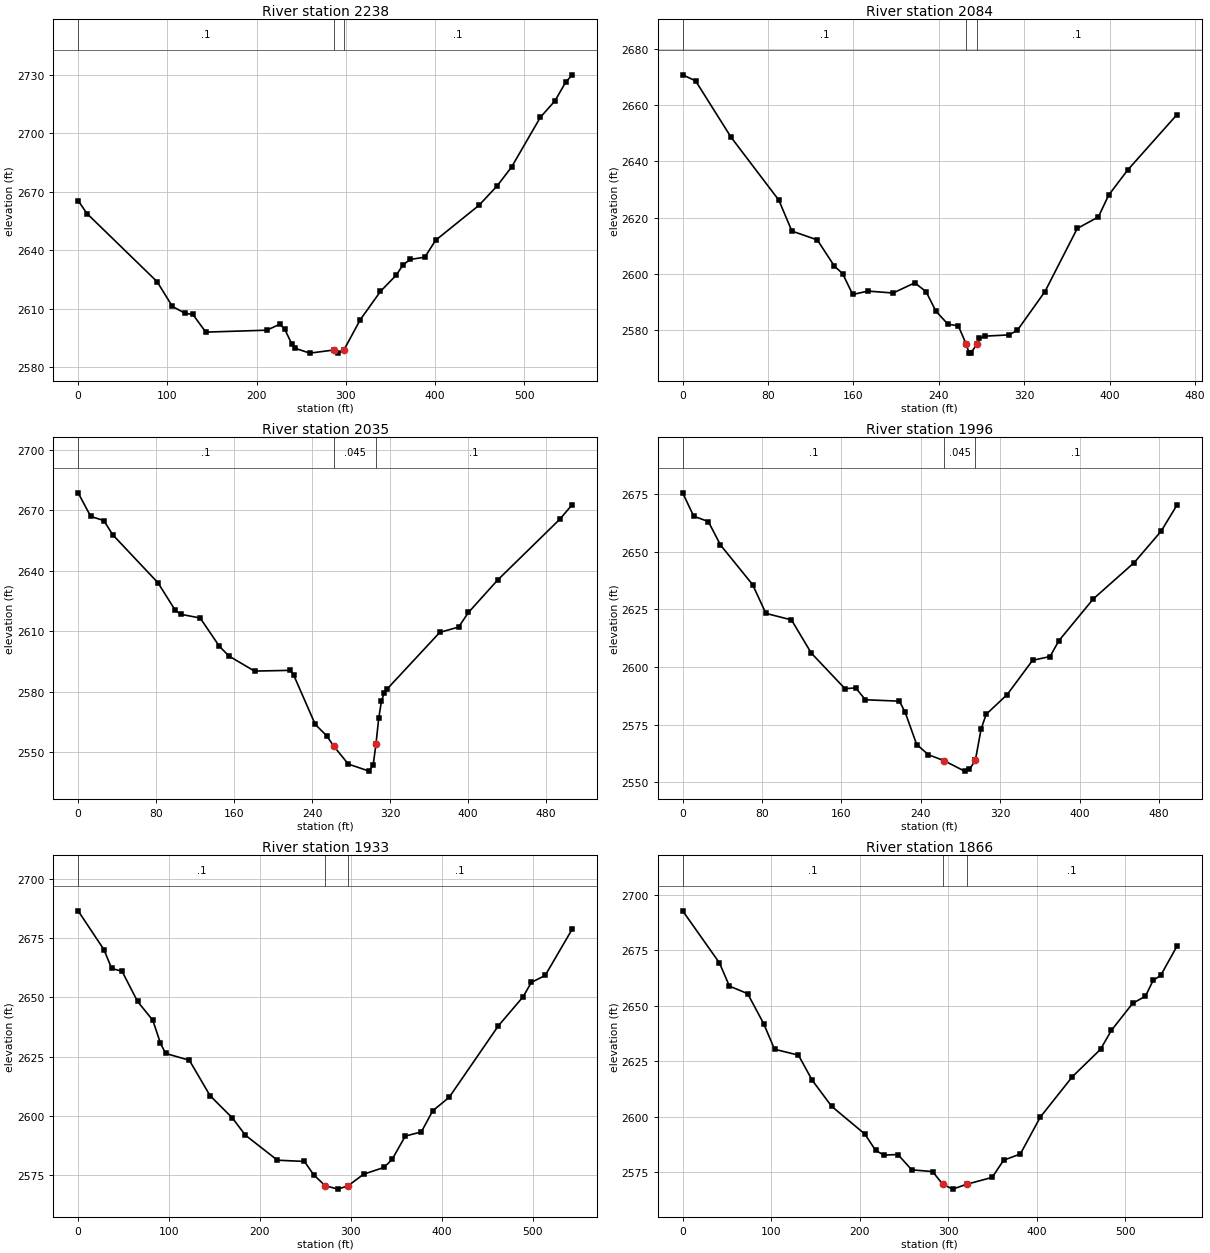
Type RM Length L Ch R = 1 ,2238    ,152.3,153.9,157.7
XS GIS Cut Line= 4
2222934.15942086541819.1008056582222848.01639628541931.809916843
2222837.48403414542100.3584666582222801.48823721542340.550185461
#Sta/Elev= 30
       0 2665.44     9.9 2658.78    88.5 2623.77   105.6 2611.07   119.9 2607.55
   128.5 2606.99     143 2597.89   211.4 2598.88     226 2601.94   231.4 2599.45
   239.4 2591.73   243.4 2589.54   259.5  2587.1   286.3 2588.69   291.5 2587.13
   297.7 2588.69   316.1 2604.28   338.7 2618.81   356.1 2627.03   364.1 2632.47
   372.2 2635.23   388.4 2636.37   400.5 2645.06   449.1 2663.03   469.3 2672.94
   485.5 2682.61   517.8  2708.2   534.2 2716.65   546.2 2726.26   553.6 2730.02
#Mann= 3, -1 ,  0
       0     0.1       0   286.3   0.045       0   297.7     0.1       0
Bank Sta=286.3,297.7
XS Rating Curve= 0 ,0
Exp/Cntr(USF)=0,0
Exp/Cntr=0.3,0.1

Type RM Length L Ch R = 1 ,2084    ,49.1,49,57.2
XS GIS Cut Line= 4
2222890.44054808541779.0182842252222775.57629247541958.419673145
2222704.07646183542032.5214626742222634.50003758542161.937822147
#Sta/Elev= 30
       0 2670.78    12.1 2668.64    45.3 2648.63    90.1 2626.25   102.3 2615.27
   126.1 2612.14   142.2 2602.78   149.8 2600.19   159.3 2592.74   173.6 2593.95
   197.1 2593.27   217.4 2596.88     228 2593.75   237.2 2586.82   248.5 2582.18
   258.2 2581.61   265.62575.097   268.3    2572   269.8 2571.91   275.5 2574.98
     278 2577.11   283.6 2577.95   305.8 2578.39   313.6 2580.06   339.4  2593.8
   369.6 2616.19   389.4  2620.3   399.1 2628.08   416.8 2636.94   462.9 2656.59
#Mann= 3, -1 ,  0
       0     0.1       0   265.6   0.045       0   275.5     0.1       0
Bank Sta=265.6,275.5
XS Rating Curve= 0 ,0
Exp/Cntr(USF)=0,0
Exp/Cntr=0.3,0.1

Type RM Length L Ch R = 1 ,2035    ,41.6,39,38.5
XS GIS Cut Line= 4
2222854.89305679541745.7189356782222790.54348678541871.544992595
2222665.96568071542002.0760283422222576.97689885542164.286556932
#Sta/Elev= 30
       0 2678.65    12.9 2666.95    26.4 2664.88    35.3 2657.93    81.9 2633.98
    99.7 2620.27   105.7 2618.31   125.2  2616.5   144.8 2602.49   154.6 2597.65
   180.9 2590.15   217.7 2590.52     221 2588.24   243.2 2563.67   254.8  2558.1
262.29372552.796   277.1 2543.99   298.4 2540.49   302.6 2543.55   305.4 2553.75
   308.3 2566.83   311.1 2575.29   313.9  2579.3   316.7 2581.16   370.9 2609.37
   390.2 2612.02   400.3 2619.26   430.2 2635.34   494.1 2665.59   506.8 2672.85
#Mann= 3, -1 ,  0
       0     0.1       0262.2937   0.045       0   305.4     0.1       0
Bank Sta=262.2937,305.4
XS Rating Curve= 0 ,0
Exp/Cntr(USF)=0,0
Exp/Cntr=0.3,0.1

Type RM Length L Ch R = 1 ,1996    ,63.1,63.1,65.3
XS GIS Cut Line= 4
2222828.49050371541732.2198021272222699.10923069541909.844939671
2222628.39358233541986.5479208692222544.17321102542138.859204114
#Sta/Elev= 30
       0 2675.57    11.1 2665.46    25.9 2663.09    38.1 2652.97    70.5 2635.76
    83.9 2623.29   109.7 2620.45   129.6 2606.09   163.6 2590.63   174.4 2590.96
   184.2 2585.82   218.5 2585.21   224.3 2580.33   235.9  2566.4   247.7    2562
   263.8 2559.34   284.1 2554.87     289 2555.62     295 2559.49     295 2559.54
   300.8 2573.09   305.9 2579.51   327.1 2588.07   352.7 2602.93   370.3 2604.57
   379.2 2611.44   413.9 2629.56   455.1  2645.3   482.2 2658.89   498.1 2670.17
#Mann= 3, -1 ,  0
       0     0.1       0   263.8   0.045       0     295     0.1       0
Bank Sta=263.8,295
XS Rating Curve= 0 ,0
Exp/Cntr(USF)=0,0
Exp/Cntr=0.3,0.1

Type RM Length L Ch R = 1 ,1933    ,68.9,67.3,66.5
BEGIN DESCRIPTION:
structure xs 4
END DESCRIPTION:
XS GIS Cut Line= 3
2222822.47812572541703.3066554732222575.90030313541946.061566089
2222483.77726021542121.090320005
#Sta/Elev= 30
       0 2686.51    28.4 2670.14    36.9 2662.19    48.3 2661.03    65.4 2648.28
    82.2 2640.33    90.6 2630.65    96.3 2626.36   122.4 2623.47   145.2 2608.53
   169.8 2599.09     184 2591.89   219.3 2581.31     249 2580.79   259.2 2575.17
   271.7  2570.6   285.8 2569.11   297.1 2570.52   314.1 2575.39   336.7 2578.29
   345.6 2581.69     360 2591.48   377.7 2593.25   390.2 2602.15   408.3 2607.84
   462.5 2638.03   489.7 2650.27   498.7 2656.31     514 2659.27   543.8 2678.85
#Mann= 3, -1 ,  0
       0     0.1       0   271.7   0.045       0   297.1     0.1       0
Bank Sta=271.7,297.1
XS Rating Curve= 0 ,0
Exp/Cntr(USF)=0,0
Exp/Cntr=0.3,0.1

Type RM Length L Ch R = 1 ,1866    ,60.1,60.6,60.4
XS GIS Cut Line= 4
2222785.91248817541656.3705486172222598.22192614541823.338177923
2222545.51148306541887.4964309392222440.15867448 542085.29603822
#Sta/Elev= 30
       0 2692.82    41.5 2669.38    52.8 2658.92    73.4 2655.51    91.5 2642.01
   103.8 2630.47   130.8 2627.81   146.3 2616.53   168.3 2604.76   205.8 2592.27
   217.9 2584.95   227.2 2582.78   243.2 2583.03   258.8 2576.13   282.4 2575.36
   293.8 2569.61   305.1 2567.45   320.9 2569.65   349.7 2572.74   362.6 2580.47
   381.5 2583.28   404.1 2599.93   440.4 2618.15   472.1 2630.44   484.3 2638.94
   508.4 2651.15   522.8 2654.36   531.6 2661.51   540.1 2663.73   558.3 2676.78
#Mann= 3, -1 ,  0
       0     0.1       0   293.8   0.045       0   320.9     0.1       0
Bank Sta=293.8,320.9
XS Rating Curve= 0 ,0
Exp/Cntr(USF)=0,0
Exp/Cntr=0.3,0.1