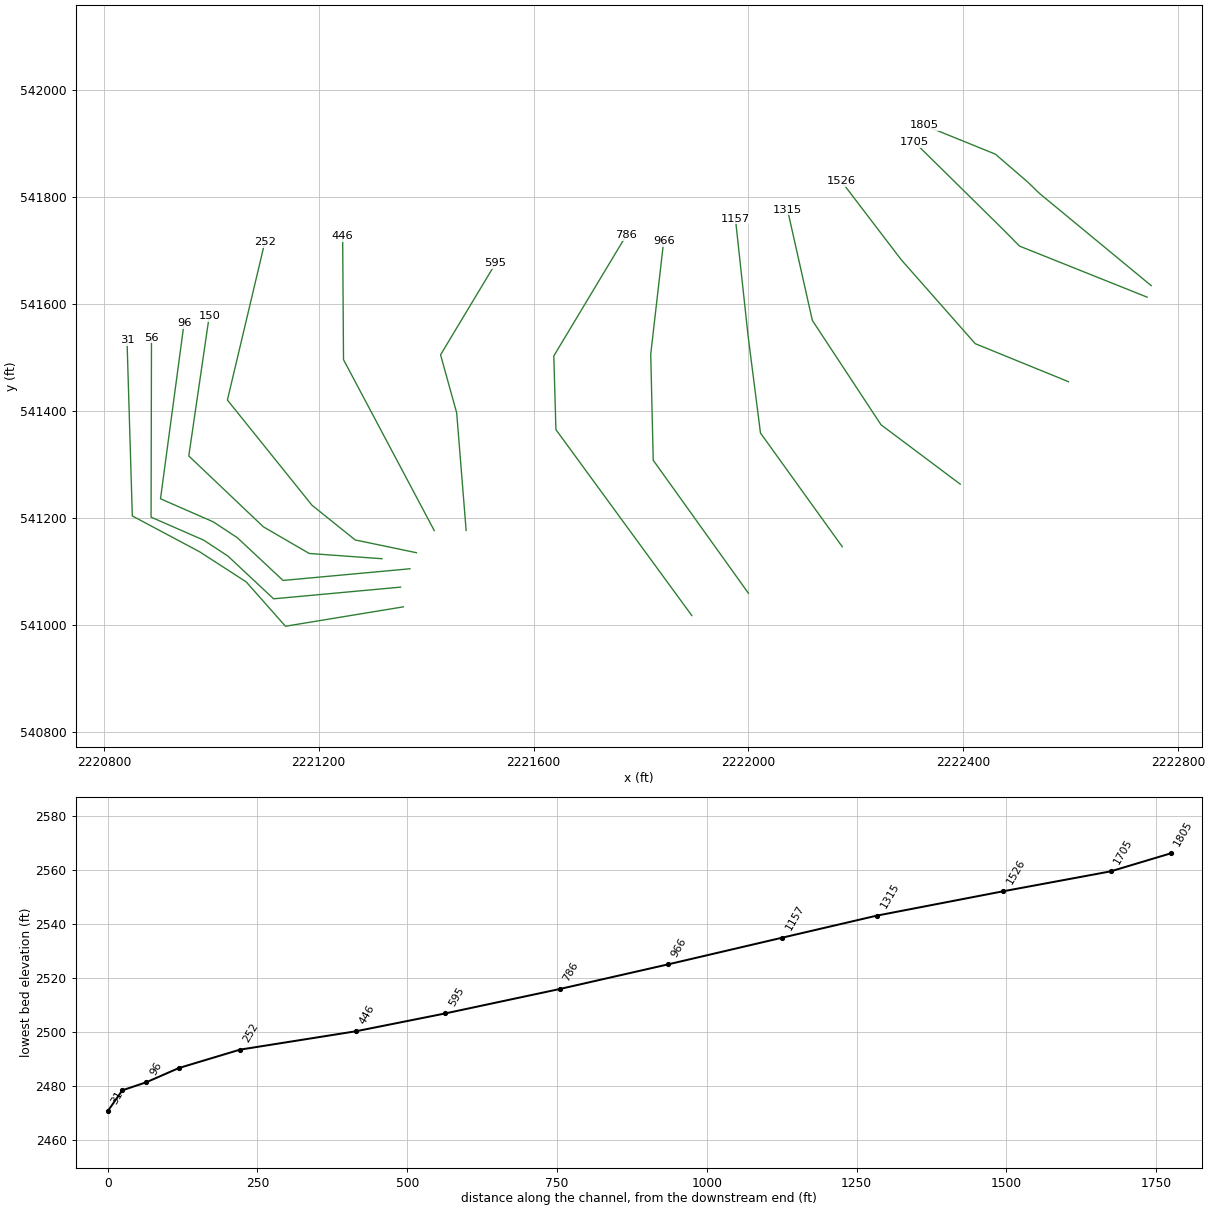
HEC-RAS study FALLSPRN.prj: FALLSPRN

--- FALLSPRN.g01 (geometry) --- (continued)

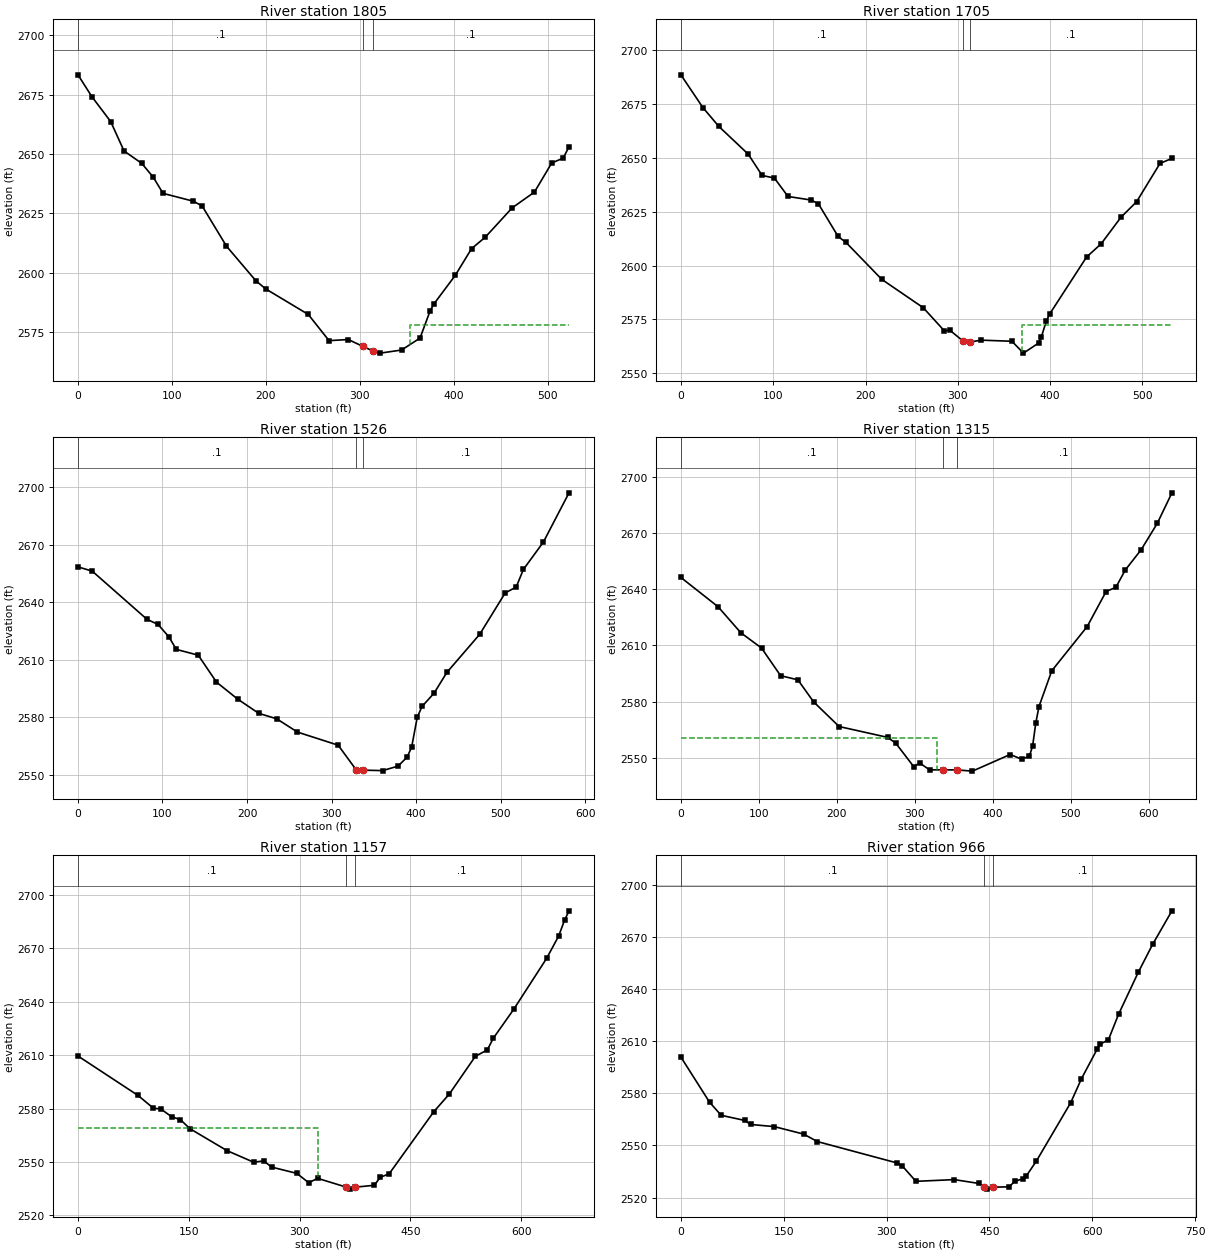
Type RM Length L Ch R = 1 ,1805    ,100.1,100,100.5
BEGIN DESCRIPTION:
structure xs 3
END DESCRIPTION:
XS GIS Cut Line= 5
2222749.87903899541633.8714466592222541.90556511541806.131411289
2222520.04013593541827.3847290212222459.86596615541879.524030502
2222328.10694167541933.147821112
#Sta/Elev= 30
       0 2683.39    14.9 2674.12    34.8 2663.68      49 2651.28    67.9 2646.02
    80.1 2640.21    90.5 2633.39   122.9 2630.06   132.1 2628.07     158 2611.11
   189.2 2596.55   199.6 2593.12     245 2582.32   267.1 2571.27   287.6 2571.73
   302.92568.883   313.82566.887   321.5    2566   344.3 2567.31   363.9 2572.35
   374.5 2583.66   378.3 2586.54   401.4 2598.81   418.7 2610.05   433.4 2614.94
   461.9 2627.27   485.6 2633.92     504 2646.19   516.2 2648.26   522.4 2653.04
#Mann= 3, -1 ,  0
       0     0.1       0   302.9   0.045       0   313.8     0.1       0
#XS Ineff= 2 , 0
                          352.98         2577.86
Permanent Ineff=
       F       F
Bank Sta=302.9,313.8
XS Rating Curve= 0 ,0
Exp/Cntr(USF)=0,0
Exp/Cntr=0.3,0.1

Type RM Length L Ch R = 1 ,1705    ,179.8,179.5,179.3
BEGIN DESCRIPTION:
structure xs 2
END DESCRIPTION:
XS GIS Cut Line= 4
2222742.22843013541612.4049996692222504.89663359541707.668312609
2222475.74077563 541737.288131752222308.91069887541902.267241831
#Sta/Elev= 30
       0 2688.64    23.8 2673.45      41 2664.72    72.9  2651.8      88  2641.9
   101.3 2640.68     116 2632.13   140.6  2630.5   148.8 2628.83   170.3 2613.55
   178.9 2610.75   217.7 2593.58   262.5 2580.46   285.3 2569.74   291.5 2569.95
   306.12564.792   313.52564.522   325.2 2565.38   358.6 2564.86   371.1 2559.35
   387.4 2564.01   390.3 2566.67   395.9  2574.3   399.5 2577.54   439.4 2603.96
   455.3 2610.17   476.7 2622.47   493.6 2629.67     519  2647.5   531.9  2649.8
#Mann= 3, -1 ,  0
       0     0.1       0   306.1   0.045       0   313.5     0.1       0
#XS Ineff= 2 , 0
                          369.94          2572.4
Permanent Ineff=
       F       F
Bank Sta=306.1,313.5
XS Rating Curve= 0 ,0
Exp/Cntr(USF)=0,0
Exp/Cntr=0.3,0.1

Type RM Length L Ch R = 1 ,1526    ,211.2,210.7,209.6
BEGIN DESCRIPTION:
structure xs 1
END DESCRIPTION:
XS GIS Cut Line= 4
2222595.82830867541454.4481581442222422.22005431541525.493135719
2222284.17045509541682.6572948222222172.64128499541829.321081501
#Sta/Elev= 30
       0 2658.48    16.9 2656.25    81.7 2631.11    94.7 2628.48   107.7 2621.93
   116.3 2615.45   142.3 2612.43   163.9 2598.38   188.8 2589.58   213.8 2582.12
   235.1 2579.26   259.7 2572.33   307.9 2565.49  329.422552.497   330.5 2551.97
   336.9 2552.48   360.4 2552.24   378.8 2554.59   389.5 2559.33   394.8 2564.46
   401.4 2580.04   407.1 2585.69   421.4 2592.66   436.4  2603.4   475.3 2623.29
   505.5 2644.89   518.5 2647.95     527 2657.13   550.7 2671.43     581 2697.09
#Mann= 3, -1 ,  0
       0     0.1       0  329.42   0.045       0   336.9     0.1       0
Bank Sta=329.42,336.9
XS Rating Curve= 0 ,0
Exp/Cntr(USF)=0,0
Exp/Cntr=0.3,0.1

Type RM Length L Ch R = 1 ,1315    ,160.8,158.2,153.7
XS GIS Cut Line= 4
2222394.33501598541263.0070482692222246.84612793541373.918692081
2222119.00995723541568.8975861872222072.78375397541775.505566147
#Sta/Elev= 30
       0 2646.29    47.7 2630.64    76.8  2616.8   103.4 2608.61   127.8 2593.88
     150 2591.66     170 2579.97   202.8 2566.75     265 2560.97   275.5 2557.83
   298.4 2545.37   306.1  2547.3   318.8 2543.63  336.432543.639   353.3 2543.62
   373.7 2542.96   422.1 2551.83     437 2549.27   446.7    2551   450.8 2556.26
   454.9  2568.6     459 2577.43   475.4  2596.5   520.8  2620.1     545 2638.77
   557.6 2641.05   569.6 2650.25   590.1 2661.16   610.6 2675.13   629.4 2691.43
#Mann= 3, -1 ,  0
       0     0.1       0  336.43   0.045       0   353.3     0.1       0
#XS Ineff= 2 , 0
          327.69 2560.69
Permanent Ineff=
       F       F
Bank Sta=336.43,353.3
XS Rating Curve= 0 ,0
Exp/Cntr(USF)=0,0
Exp/Cntr=0.3,0.1

Type RM Length L Ch R = 1 ,1157    ,190.8,190.6,189.6
XS GIS Cut Line= 4
 2222174.6284733541146.1666600242222022.41994084541358.550658814
2221999.46892799541539.2211943562221975.73830368541759.177002647
#Sta/Elev= 30
       0 2609.57    81.3  2587.4   102.1 2580.23     112 2579.87   126.7 2575.45
   138.7 2573.81   151.3 2568.79   201.7 2556.41   237.7 2549.91   251.4 2550.61
   262.1 2547.16   296.2 2543.63   312.3 2538.38   324.4 2540.83   363.4 2535.87
   368.8 2534.78  374.952535.874     401 2536.93   409.1 2541.42   421.2 2543.38
   481.6 2578.28   502.7 2588.24   537.9 2609.41     554 2612.96   562.1 2619.52
   589.8 2635.81   634.5 2664.55   650.6 2676.98   658.6 2685.89   664.6 2691.12
#Mann= 3, -1 ,  0
       0     0.1       0   363.4   0.045       0  374.95     0.1       0
#XS Ineff= 2 , 0
          324.98 2569.34
Permanent Ineff=
       F       F
Bank Sta=363.4,374.95
XS Rating Curve= 0 ,0
Exp/Cntr(USF)=0,0
Exp/Cntr=0.3,0.1

Type RM Length L Ch R = 1 ,966     ,180.2,180.2,180.2
XS GIS Cut Line= 4
2222000.01850053 541059.161312932221822.75049136541307.690897647
2221818.11033672541505.8266397892221842.23470795541717.144341527
#Sta/Elev= 30
       0 2600.91    41.8 2574.93    58.7 2567.39    93.1 2564.42   101.7  2562.1
   136.1 2560.88   179.1 2556.56     199 2552.27   314.8    2540   322.8  2538.3
   342.8 2529.38   398.8 2530.36   434.8 2528.15  441.772525.962   446.8 2524.89
   454.8 2525.99   478.8 2526.22   486.8 2529.33   498.8 2530.87   503.5 2532.28
   518.6 2541.11   568.6 2574.66   584.2 2588.39   607.5 2605.71   611.5 2608.27
   623.6 2610.87   638.4 2625.55   667.3 2649.82     688 2665.72   716.2 2685.06
#Mann= 3, -1 ,  0
       0     0.1       0  441.77   0.045       0   454.8     0.1       0
Bank Sta=441.77,454.8
XS Rating Curve= 0 ,0
Exp/Cntr(USF)=0,0
Exp/Cntr=0.3,0.1

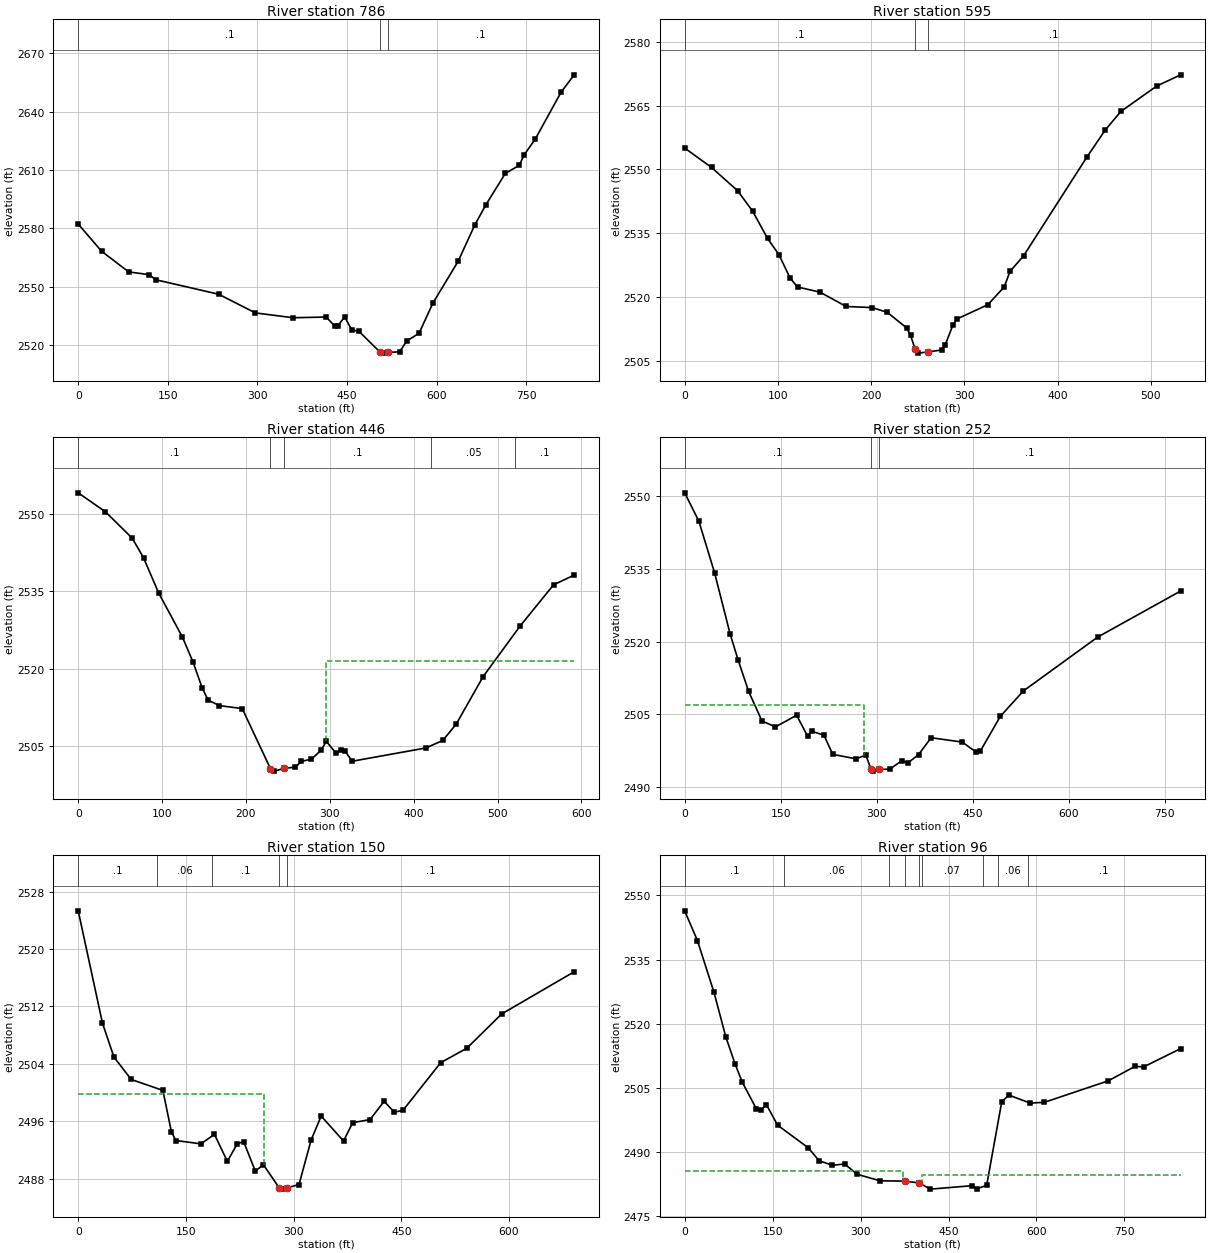
Type RM Length L Ch R = 1 ,786     ,191,191.4,194.1
XS GIS Cut Line= 4
2221894.62627506541017.4575036782221641.60089379541364.875773304
2221637.66785677541502.5320688162221772.70212761541728.026190988
#Sta/Elev= 30
       0 2582.19    39.2 2568.19    84.6 2557.57   118.4 2556.19   130.4 2553.51
   235.2 2546.09   296.6 2536.49   359.5 2534.01   415.3 2534.36   430.1  2529.5
   434.1 2529.67   446.1 2534.42   458.1 2527.69   470.1    2527  505.91 2516.15
   510.1  2515.8   518.1 2516.14   538.1 2516.48   550.1 2522.08   570.6    2526
   593.9 2541.58   635.9 2562.95   663.8 2581.64   682.5  2592.1   715.1 2608.26
   738.4 2612.39   746.2  2617.6   765.5 2626.08   808.4 2650.03   830.3 2658.97
#Mann= 3, -1 ,  0
       0     0.1       0  505.91   0.045       0   518.1     0.1       0
Bank Sta=505.91,518.1
XS Rating Curve= 0 ,0
Exp/Cntr(USF)=0,0
Exp/Cntr=0.3,0.1

Type RM Length L Ch R = 1 ,595     ,148.5,149,152
XS GIS Cut Line= 4
2221474.45700458541176.520654268  2221456.863219541396.075890548
2221426.86680047541504.6586232012221529.12633314541675.304352191
#Sta/Elev= 30
       0 2555.04    28.8 2550.47    56.8 2544.98    72.9 2540.16    88.9 2533.74
     101 2529.96     113 2524.44     121 2522.32   145.1  2521.1   173.2 2517.73
   201.3 2517.46   217.4 2516.32     238 2512.68   242.2 2510.92     2472507.795
   250.5 2506.74   260.7 2507.02   275.4 2507.47   279.5 2508.76   287.8 2513.44
     292 2514.79   325.1 2518.14   342.8 2522.38   348.8 2525.98   363.4 2529.65
   431.4 2552.95   450.9 2559.26   467.7 2563.66   506.1 2569.64   531.8 2572.29
#Mann= 3, -1 ,  0
       0     0.1       0     247   0.045       0   260.7     0.1       0
Bank Sta=247,260.7
XS Rating Curve= 0 ,0
Exp/Cntr(USF)=0,0
Exp/Cntr=0.3,0.1

Type RM Length L Ch R = 1 ,446     ,193.2,193.6,195.8
XS GIS Cut Line= 3
2221415.07701541541176.2791098362221246.16062102541495.597382584
2221244.57646446541725.793398489
#Sta/Elev= 30
       0 2554.12    32.4 2550.45    64.4 2545.32    77.9 2541.52      96 2534.67
   124.2 2526.16   136.8 2521.35   147.8 2516.29   154.9 2513.91   168.4 2512.85
   195.6 2512.27  229.162500.648   233.7 2500.14   245.7 2500.67     259 2500.92
   266.2 2502.04   278.1 2502.46   289.9 2504.24   295.8 2505.92   307.7 2503.57
   313.6 2504.27   317.8 2504.09   326.8 2502.06   414.8 2504.64   434.8  2506.1
   450.8 2509.27   482.8 2518.46   526.8 2528.25   566.8 2536.27   591.4 2538.16
#Mann= 5, -1 ,  0
       0     0.1       0  229.16   0.045       0   245.7     0.1       0
  421.24    0.05       0  521.24     0.1       0
#XS Ineff= 2 , 0
                          295.88         2521.41
Permanent Ineff=
       F       F
Bank Sta=229.16,245.7
XS Rating Curve= 0 ,0
Exp/Cntr(USF)=0,0
Exp/Cntr=0.3,0.1

Type RM Length L Ch R = 1 ,252     ,101.9,102.1,103.4
XS GIS Cut Line= 5
2221381.88896179541134.919419059 2221267.8792455 541158.78101609
2221187.44849212 541223.645225192221030.02286308541420.186253035
2221099.69829452541715.291869645
#Sta/Elev= 30
       0 2550.66    22.2 2544.81    46.7 2534.19    71.2 2521.48    83.5 2516.23
    99.8 2509.78   120.8 2503.65   141.8 2502.45   174.9 2504.84   191.9 2500.57
   198.3 2501.54   217.5 2500.75   231.4 2496.78   267.9 2495.86     283 2496.65
  290.992493.767   293.5 2493.33   302.9 2493.72     320 2493.71   339.6  2495.5
   348.4    2495   365.3 2496.72     385 2500.21   433.8 2499.31   455.4 2497.22
   461.8 2497.43   493.2 2504.63   529.2 2509.85   645.3 2520.95   774.8 2530.43
#Mann= 3, -1 ,  0
       0     0.1       0  290.99   0.045       0   302.9     0.1       0
#XS Ineff= 2 , 0
          280.14  2506.9
Permanent Ineff=
       F       F
Bank Sta=290.99,302.9
XS Rating Curve= 0 ,0
Exp/Cntr(USF)=0,0
Exp/Cntr=0.3,0.1

Type RM Length L Ch R = 1 ,150     ,52.1,54,57.3
BEGIN DESCRIPTION:
structure xs 4
END DESCRIPTION:
XS GIS Cut Line= 5
2221317.75786381541123.6778633822221182.24638477541133.538312576
2221096.81522145541183.4012918512220958.10854814541315.680840491
2220996.18804215541577.139324207
#Sta/Elev= 30
       0 2525.34    33.7 2509.71    49.7 2504.95    73.8 2501.82   117.9 2500.29
   129.8 2494.52   135.9  2493.3   170.7 2492.84   189.8 2494.15   207.7 2490.39
   221.6 2492.86   230.4 2493.14   246.7 2489.02   257.8 2489.94   279.9  2486.7
   283.7 2486.52   290.3 2486.69   307.5 2487.16   324.3 2493.35   338.4 2496.71
   369.5 2493.23   382.3  2495.8   406.3 2496.21   426.1 2498.77   440.1 2497.26
   452.2  2497.5   504.8 2504.16   541.2 2506.17   589.7 2510.95   690.7 2516.84
#Mann= 5, -1 ,  0
       0     0.1       0     110    0.06       0  185.87     0.1       0
   279.9   0.045       0   290.3     0.1       0
#XS Ineff= 2 , 0
          259.28 2499.83
Permanent Ineff=
       F       F
Bank Sta=279.9,290.3
XS Rating Curve= 0 ,0
Exp/Cntr(USF)=0,0
Exp/Cntr=0.3,0.1

Type RM Length L Ch R = 1 ,96      ,44,40.3,40.9
BEGIN DESCRIPTION:
structure xs 3
END DESCRIPTION:
XS GIS Cut Line= 6
 2221369.9302597541104.9270844512221133.58717401541083.092923462
2221048.58354011541162.8966523342221003.50414658541192.662914352
2220905.44645434541235.6706741072220949.32788052541563.570952635
#Sta/Elev= 30
       0 2546.41    21.8 2539.42      50 2527.34    70.1 2516.93    86.1 2510.51
    98.2 2506.32   122.3 2500.06   130.3 2499.74   139.4 2501.07   158.4 2496.26
   210.6 2490.97   229.4 2487.92   251.9 2486.87   272.6 2487.16   294.7 2484.73
   333.3 2483.23     3752483.151     4002482.734   419.2 2481.28   489.8 2482.08
   498.9 2481.36   515.1 2482.18   540.8 2501.72   552.9 2503.29   589.2 2501.42
   613.4 2501.59   722.4 2506.62     768    2510   782.9 2509.89   845.9 2514.16
#Mann= 9, -1 ,  0
       0     0.1       0     170    0.06       0  347.71     0.1       0
     375   0.045       0     400     0.1       0  403.97    0.07       0
  507.99     0.1       0  535.06    0.06       0  585.06     0.1       0
#XS Ineff= 2 , 0
          372.01 2485.62  405.53         2484.59
Permanent Ineff=
       F       F
Bank Sta=375,400
XS Rating Curve= 0 ,0
Exp/Cntr(USF)=0,0
Exp/Cntr=0.3,0.1

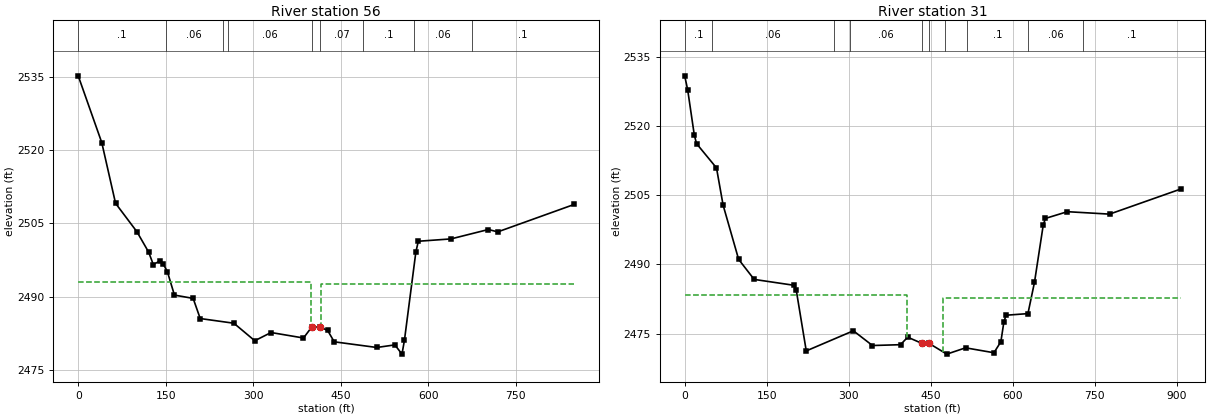
Type RM Length L Ch R = 1 ,56      ,22.5,24.5,22.3
BEGIN DESCRIPTION:
structure xs 2
END DESCRIPTION:
XS GIS Cut Line= 6
2221352.37361546541070.6208756952221116.03052978541048.786714706
2221031.02689587541128.5904435782220985.94750234541158.356705596
 2220887.8898101541201.3644653512220888.65517495541536.283637583
#Sta/Elev= 30
       0  2535.2    40.4 2521.53      64 2509.12   100.6 2503.31   120.7 2499.14
   128.7 2496.59   140.8  2497.4   146.1 2496.62   152.8 2495.15   164.9 2490.35
     197 2489.67   209.1 2485.55   266.8 2484.59   302.6 2481.01   330.5 2482.69
   386.1 2481.57   400.5 2483.85     415 2483.77   427.4 2483.13   438.8 2480.79
   511.7 2479.63   542.7 2480.16   554.9 2478.27   559.1 2481.08   578.7 2499.16
   582.9 2501.36   638.9 2501.84   702.9 2503.76   719.1 2503.28     850 2508.89
#Mann= 9, -1 ,  0
       0     0.1       0     150    0.06       0  247.35     0.1       0
  257.35    0.06       0   400.5   0.045       0     415    0.07       0
  487.99     0.1       0  575.06    0.06       0  675.06     0.1       0
#XS Ineff= 2 , 0
          399.72 2493.01  416.35          2492.6
Permanent Ineff=
       F       F
Bank Sta=400.5,415
XS Rating Curve= 0 ,0
Exp/Cntr(USF)=0,0
Exp/Cntr=0.3,0.1

Type RM Length L Ch R = 1 ,31      ,,,
BEGIN DESCRIPTION:
structure xs 1
END DESCRIPTION:
XS GIS Cut Line= 6
2221357.56571651541033.7734372512221138.09711847540997.543700433
2221064.94091913541080.4540596892220978.13476466541136.733938513
2220852.98268223541203.6345211692220843.08133769541532.301733808
#Sta/Elev= 30
       0 2530.97     5.5 2527.92    17.6 2518.11    21.7 2516.24    58.2 2510.97
    70.3 2502.88    98.7  2491.1   127.1 2486.75   200.1 2485.47   204.1 2484.41
   222.4 2471.22   308.6 2475.59   343.5 2472.39   394.8 2472.57   407.9  2474.2
     434 2472.86   447.1 2472.85   479.5 2470.52   513.8 2471.89   565.7 2470.82
   578.4 2473.21   583.9 2477.51   587.9 2478.97   627.9 2479.32   639.9 2486.13
     656 2498.64     660    2500     700 2501.46   777.2 2500.93   907.2 2506.37
#Mann= 10, -1 ,  0
       0     0.1       0      50    0.06       0  272.44     0.1       0
  302.44    0.06       0     434   0.045       0   447.1    0.06       0
  476.46    0.07       0  516.46     0.1       0  628.37    0.06       0
  728.37     0.1       0
#XS Ineff= 2 , 0
          407.16  2483.3  471.66         2482.79
Permanent Ineff=
       F       F
Bank Sta=434,447.1
XS Rating Curve= 0 ,0
Exp/Cntr(USF)=0,0
Exp/Cntr=0.3,0.1
LCMann Table=0

Chan Stop Cuts=-1
Use User Specified Reach Order=0
Composite Channel Slope=5